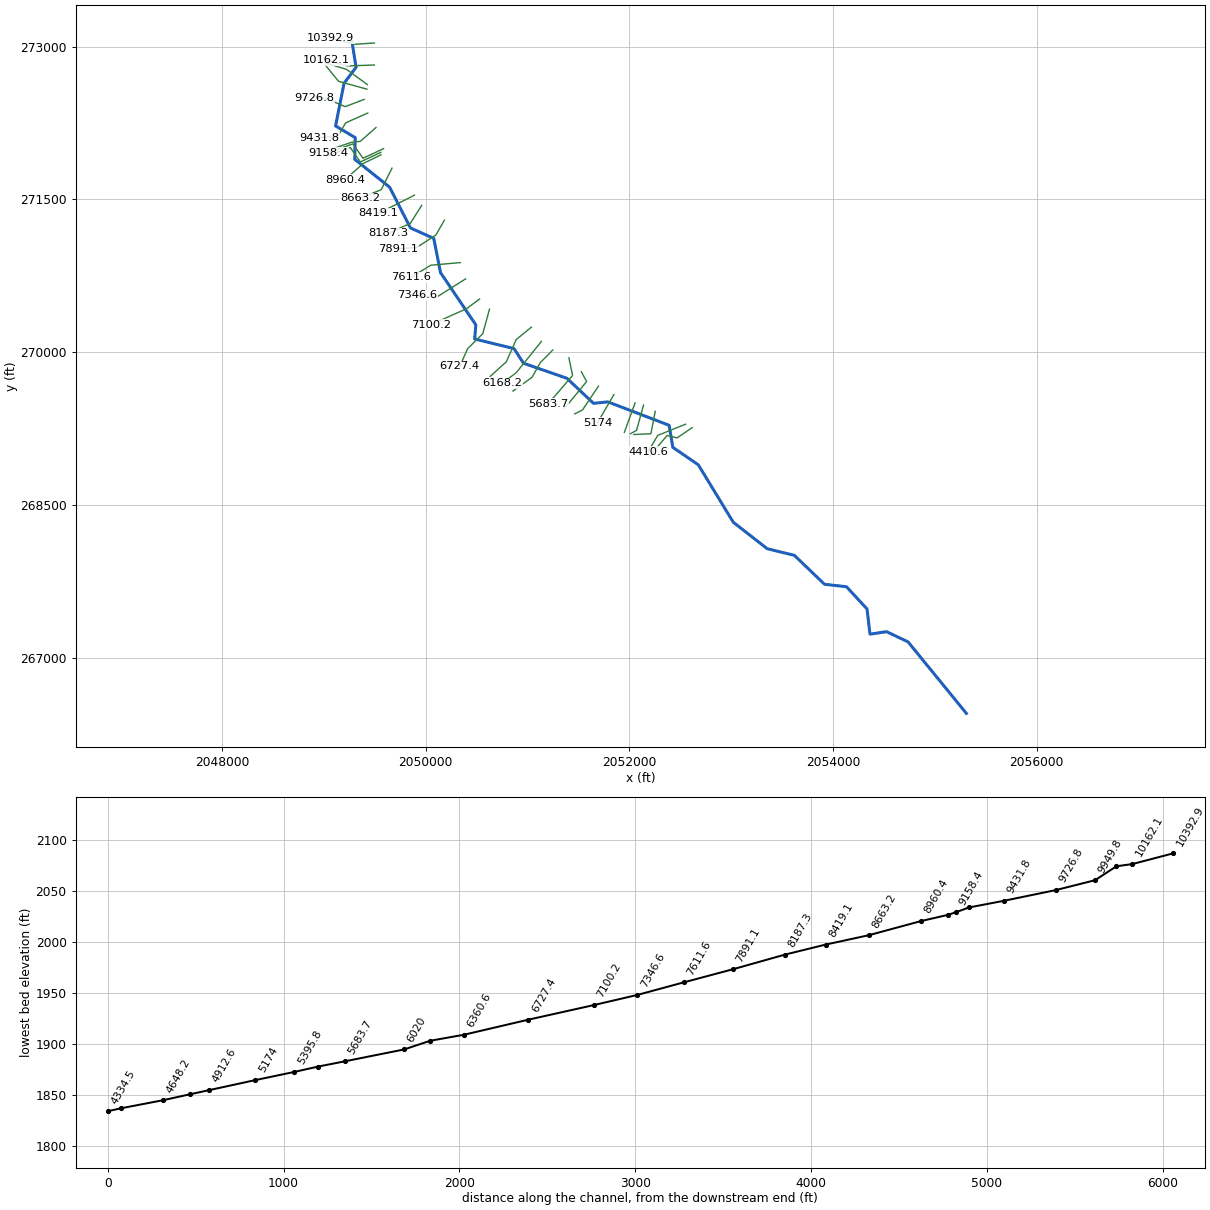
--- GRFTHCK.prj (project) ---

Proj Title=GRFTHCK
Current Plan=p01
Default Exp/Contr=0,0
English Units
Geom File=g01
Flow File=f01
Plan File=p01
BEGIN DESCRIPTION:
END DESCRIPTION:
DSS Export Rating Curves= 0
DSS Export Rating Curve Sorted= 0
DSS Export Volume Flow Curves= 0
DXF OffsetX= 0
DXF OffsetY= 0
DXF ScaleX= 0
DXF ScaleY= 0

--- GRFTHCK.p01 (plan) ---

Plan Title=Floodplain
Program Version=4.00
Geom File=g01
Flow File=f01
K Sum by GR=0
Std Step Tol=0.01
Critical Tol=0.01
Num of Std Step Trials=20
Max Error Tol=0.3
Flow Tol Ratio=0.001
Split Flow NTrial=30
Split Flow Tol=0.02
Split Flow Ratio=0.02
Log Output Level=0
Friction Slope Method=1
Unsteady Friction Slope Method=2
Unsteady Bridges Friction Slope Method=1
Global Log Level=0
CheckData=False
Run HTab=0
Run UNet=0
Run PostProcess=0
UNET Theta=0
UNET Theta Warmup=0
UNET ZTol=0
UNET ZSATol=0
UNET MxIter=0
UNET MaxInSteps=0
UNET DtIC=0
UNET DtMin=0
UNET MaxCRTS=0
UNET WFStab=0
UNET SFStab=0
UNET WFX=0
UNET SFX=0
UNET DSS MLevel=0
UNET DZMax Abort=0
UNET Convert EG Bridges=0
UNET Use Existing IB Tables=0
UNET Froude Limit=0
UNET Froude Power=0
Write IC File=0
Echo Input=False
Echo Output=False
Write Detailed=0

--- GRFTHCK.f01 (steady flow) ---

Flow Title=2010 USGS WV Regression Equation
Program Version=4.10
Number of Profiles= 1
Profile Names=P100yr
River Rch & RM=GRFTHCK,Main            ,10392.9
379.0315
River Rch & RM=GRFTHCK,Main            ,9726.8
403.1947
River Rch & RM=GRFTHCK,Main            ,7346.6
429.8254
River Rch & RM=GRFTHCK,Main            ,4912.6
476.5972
River Rch & RM=GRFTHCK,Main            ,4800.5
628.0701
River Rch & RM=GRFTHCK,Main            ,2195
645.2995
River Rch & RM=GRFTHCK,Main            ,1882.2
724.6715
River Rch & RM=GRFTHCK,Main            ,147.8
789.0615
Boundary for River Rch & Prof#=GRFTHCK,Main            , 1
Up Type= 0
Dn Type= 1
Dn Known WS=1712
DSS Import GetInterval= 0
DSS Import GetPeak= 0
DSS Import FillOption= 0

--- GRFTHCK.g01 (geometry) ---

Geom Title=LiDAR
Program Version=4.10

River Reach=GRFTHCK         ,Main
Reach XY= 30
     2049276.512      273047.418     2049316.402      272796.164
     2049198.781      272640.348      2049115.02      272220.902
     2049307.777       272106.78     2049304.149      271892.758
     2049645.392      271620.459     2049850.471      271220.069
      2050079.42      271116.987     2050145.571      270781.951
     2050492.078      270268.984      2050481.11      270130.108
     2050867.617      270035.747     2050960.933      269892.084
     2051387.149      269744.514     2051647.813      269498.593
     2051788.475      269513.254     2052390.618      269283.003
     2052426.645      269066.997     2052676.643       268895.85
     2053020.393      268331.614     2053353.596      268072.195
     2053620.318      268006.933     2053915.996      267723.119
      2054131.94      267698.941     2054333.531      267480.932
     2054362.654      267233.862     2054526.016      267257.907
     2054736.401       267157.68     2055308.988      266456.202

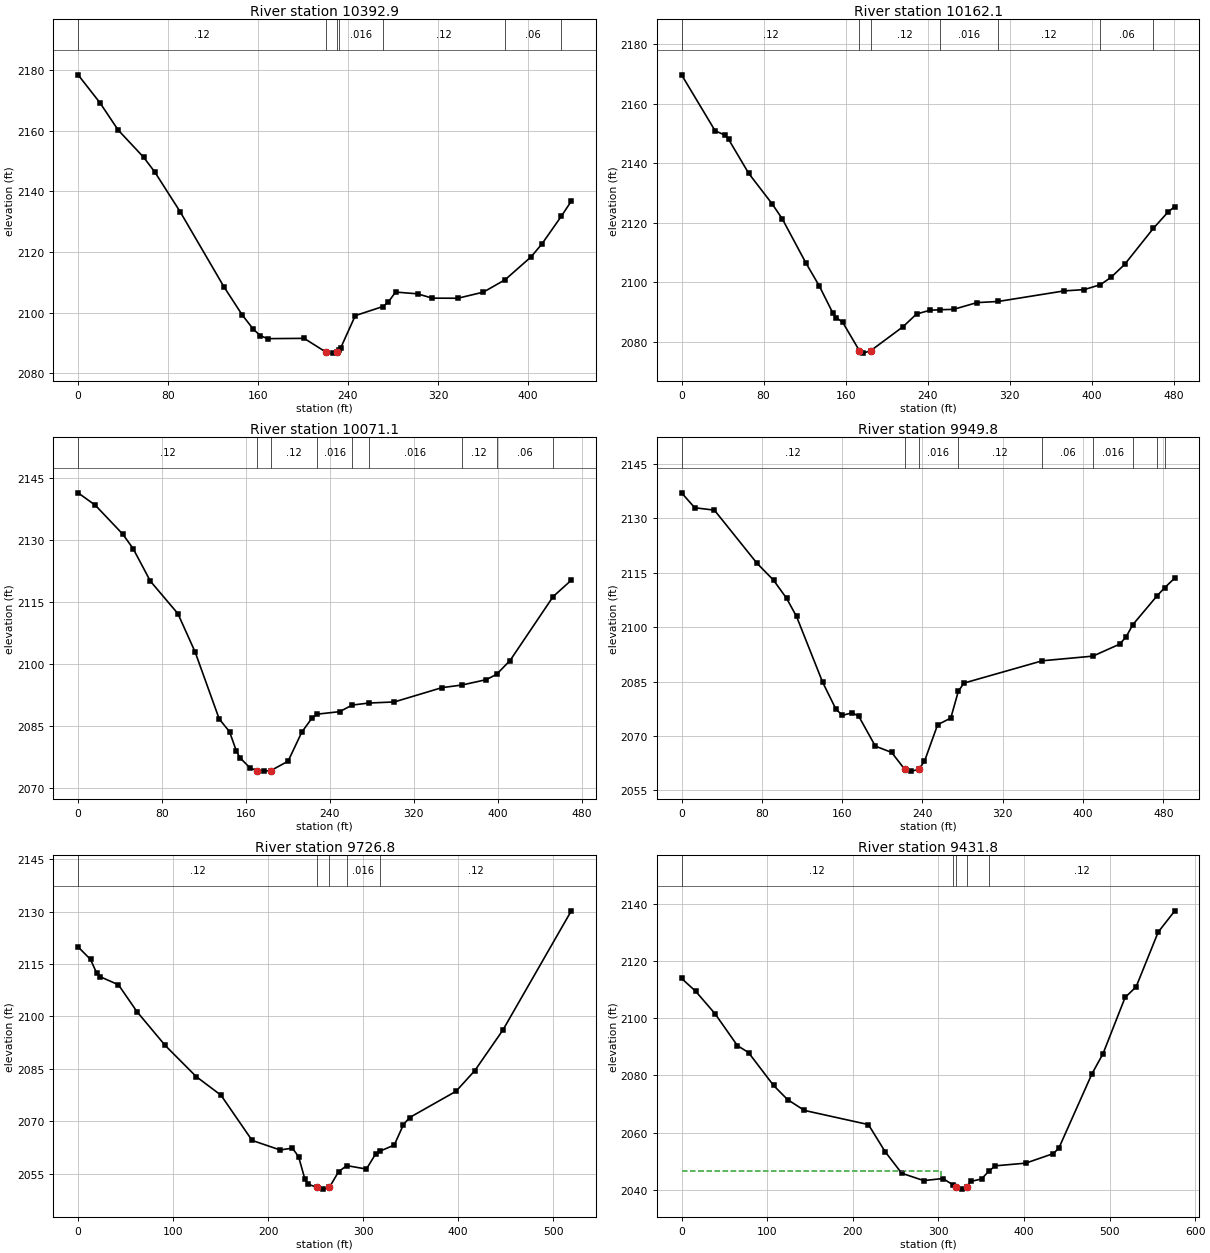
Type RM Length L Ch R = 1 ,10392.9 ,224.1,230.7,236.6
XS GIS Cut Line= 3
     2049496.519      273035.152     2049302.508      273022.132
     2049065.529      273080.725
#Sta/Elev= 30
       0 2178.56    19.4 2169.35    35.6 2160.33    58.3 2151.31    68.1  2146.5
    90.7 2133.35   129.6 2108.56   145.8 2099.29   155.6 2094.58     162 2092.36
   168.5 2091.37     201 2091.46   220.5  2086.9     227 2086.58   230.2 2086.87
  231.682087.501   233.5 2088.28   246.5 2098.98  271.112101.987   275.8 2103.43
   282.3 2106.76   301.9 2106.18   314.9 2104.75   337.7 2104.72   360.4 2106.74
  379.73 2110.84   402.8 2118.39   412.5 2122.68   429.82131.872   438.6 2136.82
#Mann= 7 ,-1 , 0
       0     .12       0   220.5    .045       0   230.2     .12       0
  231.68    .016       0  271.11     .12       0  379.73     .06       0
   429.8     .12       0
Bank Sta=220.5,230.2
XS Rating Curve= 0 ,0
Exp/Cntr=0.3,0.1

Type RM Length L Ch R = 1 ,10162.1 ,105.9,91,75.7
XS GIS Cut Line= 3
     2049495.216      272819.007     2049233.498      272809.892
     2049021.258       272864.58
#Sta/Elev= 30
       0 2169.75    32.7 2150.94    42.6 2149.42    45.8 2148.08    65.5 2136.59
    88.4 2126.32    98.2 2121.31   121.1 2106.56   134.2  2098.8   147.3 2089.78
   150.6 2088.13   157.1 2086.53   173.5 2076.92   176.8 2076.15  184.262076.919
     216 2085.04   229.1  2089.3   242.2 2090.57  251.91 2090.74   265.2 2090.87
     288 2093.14  308.67 2093.52   373.1 2097.08   392.7 2097.51  408.462099.179
   418.9 2101.67     432 2105.96     4602118.081   474.5 2123.65     481 2125.45
#Mann= 7 ,-1 , 0
       0     .12       0   173.5    .045       0  184.26     .12       0
  251.91    .016       0  308.67     .12       0  408.46     .06       0
     460     .12       0
Bank Sta=173.5,184.26
XS Rating Curve= 0 ,0
Exp/Cntr=0.3,0.1

Type RM Length L Ch R = 1 ,10071.1 ,112.7,121.3,129.2
XS GIS Cut Line= 3
     2049427.477      272626.559     2049223.559      272775.577
     2049015.719      272839.628
#Sta/Elev= 30
       0 2141.35    16.4 2138.35    42.6 2131.34    52.5 2127.82    68.9 2119.96
    95.1  2112.1   111.5 2102.83   134.5 2086.59   144.3 2083.53   150.9 2078.78
   154.2 2077.22     164 2074.71   170.6 2074.11   177.1 2073.97   183.7 2074.11
   200.1 2076.37   213.2 2083.42     223 2086.85  228.052087.769   249.3 2088.37
  261.152089.961  276.992090.454   301.3 2090.72   346.7 2094.18  365.732094.817
   388.9 2096.11   398.82097.409   411.6 2100.74  452.71 2116.24     470  2120.2
#Mann= 9 ,-1 , 0
       0     .12       0   170.6    .045       0   183.7     .12       0
  228.05    .016       0  261.15     .12       0  276.99    .016       0
  365.73     .12       0   398.8     .06       0  452.71     .12       0
Bank Sta=170.6,183.7
XS Rating Curve= 0 ,0
Exp/Cntr=0.3,0.1

Type RM Length L Ch R = 1 ,9949.8  ,225.2,223,219.6
XS GIS Cut Line= 3
       2049422.3      272582.027     2049144.956       272658.85
      2049016.05      272816.402
#Sta/Elev= 30
       0 2137.04    13.1 2132.93    32.7 2132.26    75.2  2117.6    91.6 2112.97
   104.6 2107.97   114.5 2102.97   140.6 2084.78   153.7 2077.44   160.2 2075.69
   170.1 2076.42   176.6 2075.41     193 2067.22   209.3 2065.47   222.42060.787
   228.9 2060.32  236.222060.788     242 2063.03   255.1 2073.12   268.2 2074.94
  275.682082.285   281.2 2084.58  359.382090.738  409.772092.022   436.4 2095.32
   442.9 2097.34  449.512100.674  473.552108.593  481.17 2110.84   491.4 2113.57
#Mann= 9 ,-1 , 0
       0     .12       0   222.4    .045       0  236.22    .016       0
  275.68     .12       0  359.38     .06       0  409.77    .016       0
  449.51     .12       0  473.55     .06       0  481.17     .12       0
Bank Sta=222.4,236.22
XS Rating Curve= 0 ,0
Exp/Cntr=0.3,0.1

Type RM Length L Ch R = 1 ,9726.8  ,262.2,295,327.8
XS GIS Cut Line= 4
     2049396.258      272481.767      2049210.06      272410.152
     2049036.883      272484.371     2048906.675      272499.996
#Sta/Elev= 30
       0 2119.89    13.1  2116.3    19.6 2112.37    22.9  2111.4    42.5 2109.06
    62.1 2101.33    91.6 2091.74   124.3 2082.82   150.4 2077.49   183.1 2064.58
   212.5 2061.85   225.5 2062.36     232 2059.95   238.5 2053.65   241.7 2052.07
   251.5 2051.18     258 2050.65   264.5  2051.2   274.2 2055.66  282.722057.369
   303.4 2056.39   313.2 2060.76  317.762061.514   332.7 2063.25   342.4 2069.12
   348.9 2071.12   397.7 2078.62   417.4 2084.51   446.9 2096.08     519  2130.2
#Mann= 5 ,-1 , 0
       0     .12       0   251.5    .045       0   264.5     .12       0
  282.72    .016       0  317.76     .12       0
Bank Sta=251.5,264.5
XS Rating Curve= 0 ,0
Exp/Cntr=0.3,0.1

Type RM Length L Ch R = 1 ,9431.8  ,220.1,198.7,176.7
XS GIS Cut Line= 4
     2049431.414      272347.652     2049213.966      272251.298
     2049137.144      272117.184      2048953.55      272106.767
#Sta/Elev= 30
       0 2114.03    16.3 2109.58    39.1 2101.65    65.2 2090.49    78.2 2088.04
   107.5  2076.5   123.8 2071.57   143.4 2067.76   218.3 2062.79   237.8  2053.3
   257.2 2045.73   282.9 2043.16   305.5 2043.87  317.022041.648   320.7 2040.88
     328 2040.16  332.932040.868   337.7 2042.84   350.5 2043.72  358.672046.374
   366.6 2048.33   402.1 2049.27   434.3 2052.61   440.8 2054.53   479.5  2080.6
   492.4 2087.63   518.2 2107.35   531.1 2111.09   556.9 2130.29   576.3 2137.73
#Mann= 5 ,-1 , 0
       0     .12       0  317.02    .016       0   320.7    .045       0
  332.93    .016       0  358.67     .12       0
#XS Ineff= 2 , 0
          303.41 2046.59
Permanent Ineff=
       F       F
Bank Sta=320.7,332.93
XS Rating Curve= 0 ,0
Exp/Cntr=0.3,0.1

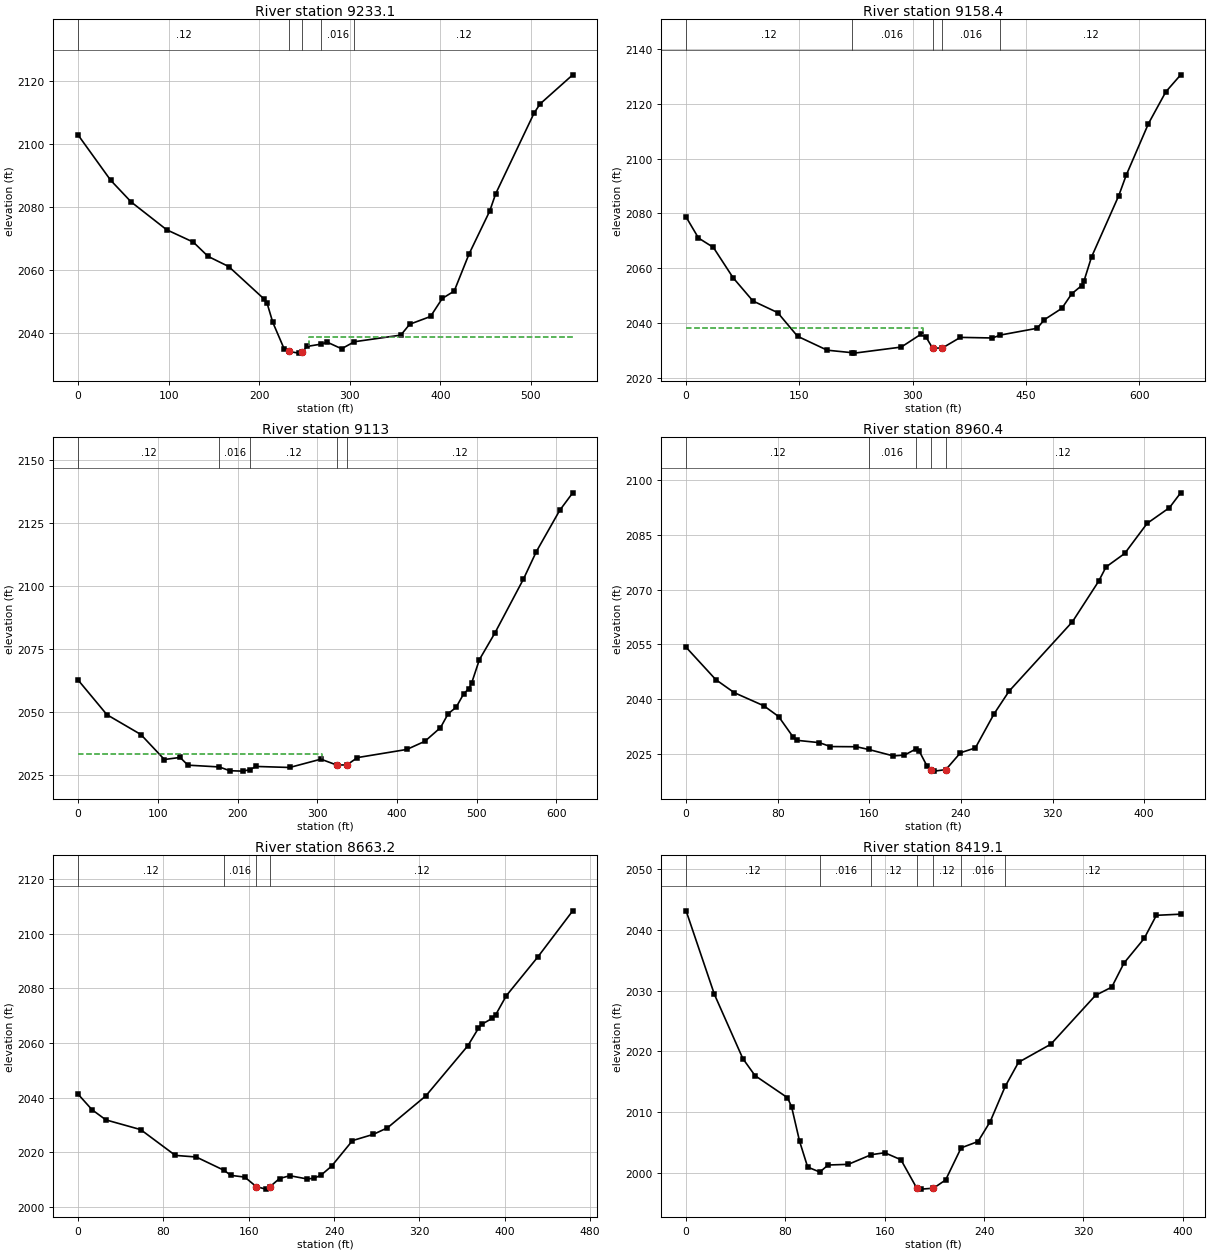
Type RM Length L Ch R = 1 ,9233.1  ,99.1,74.7,43.9
XS GIS Cut Line= 4
     2049512.022      272205.222     2049357.508      272069.806
     2049272.439      272061.125     2049031.119      271977.792
#Sta/Elev= 30
       0 2102.92    35.9 2088.57    58.7 2081.63    97.8 2072.83   127.2 2068.91
   143.5 2064.38   166.3 2061.15   205.5  2050.8   208.6 2049.59     215 2043.41
   227.6 2034.96   232.7 2034.18   243.5 2033.64   247.7 2034.07     253 2035.78
  268.722036.515   275.1 2037.12     291 2035.03  305.122037.259   356.4 2039.36
   366.2 2042.81   389.2 2045.28   402.2 2051.01   415.4 2053.36   431.7 2065.09
   454.6 2078.77   461.2 2084.28   503.7 2109.96   510.3 2112.83   546.3 2122.06
#Mann= 5 ,-1 , 0
       0     .12       0   232.7    .045       0   247.7     .12       0
  268.72    .016       0  305.12     .12       0
#XS Ineff= 2 , 0
                          255.11         2038.65
Permanent Ineff=
       F       F
Bank Sta=232.7,247.7
XS Rating Curve= 0 ,0
Exp/Cntr=0.3,0.1

Type RM Length L Ch R = 1 ,9158.4  ,48.1,45.4,51.3
XS GIS Cut Line= 4
     2049586.362      271998.694     2049384.638      271903.711
     2049285.581      272045.569     2049042.091      271957.027
#Sta/Elev= 30
       0 2078.65    16.4 2070.98    36.1 2067.56    62.3 2056.46    88.5    2048
   121.3 2043.75   147.6 2035.12   186.9 2030.03  219.582029.125     223 2028.96
     285 2031.17   311.1 2035.87   317.6 2034.91  326.442030.802  339.222030.802
   363.3 2034.71   405.8 2034.49  416.412035.569   464.9 2038.03   474.7  2041.2
   497.7 2045.31   510.8 2050.63   523.9  2053.6   527.2 2055.46     537 2064.05
   573.1 2086.47   582.9 2093.89   612.4 2112.75   635.4 2124.35   655.1 2130.56
#Mann= 5 ,-1 , 0
       0     .12       0  219.58    .016       0  326.44    .045       0
  339.22    .016       0  416.41     .12       0
#XS Ineff= 2 , 0
          313.52 2038.04
Permanent Ineff=
       F       F
Bank Sta=326.44,339.22
XS Rating Curve= 0 ,0
Exp/Cntr=0.3,0.1

Type RM Length L Ch R = 1 ,9113    ,110.8,152.5,190.9
XS GIS Cut Line= 4
     2049560.321      271962.236     2049358.596      271867.252
     2049259.539      272009.111     2049048.602      271932.288
#Sta/Elev= 30
       0 2062.49    36.1 2048.76    78.7 2040.89   108.2 2030.97   127.9  2031.8
   137.7 2028.73  177.06 2028.02   190.2 2026.52   206.6 2026.36  216.01 2026.98
     223 2028.22   265.4 2027.81   304.6 2031.11   324.2  2028.8   337.2 2028.81
   350.3 2031.73   412.3 2034.96     435  2038.2   454.6 2043.62   464.3 2049.19
   474.1 2051.64   483.8 2057.09   490.3 2059.14   493.6 2061.25   503.4 2070.61
   522.9 2081.21   558.7  2102.6   574.9 2113.52   604.2 2129.88   620.5 2136.82
#Mann= 5 ,-1 , 0
       0     .12       0  177.06    .016       0  216.01     .12       0
   324.2    .045       0   337.2     .12       0
#XS Ineff= 2 , 0
          305.57 2032.97
Permanent Ineff=
       F       F
Bank Sta=324.2,337.2
XS Rating Curve= 0 ,0
Exp/Cntr=0.3,0.1

Type RM Length L Ch R = 1 ,8960.4  ,287.9,297.2,305.2
XS GIS Cut Line= 3
     2049561.623      271937.496     2049387.144      271852.861
     2049208.758      271695.309
#Sta/Elev= 30
       0  2054.2    25.9 2045.36      42 2041.79    67.9 2038.19    80.8 2035.25
    93.7 2029.54      97 2028.74   116.4 2028.11     126 2027.04   148.7 2026.99
  159.49 2026.24     181 2024.48   190.7  2024.7  200.952026.428   203.7 2025.72
   210.2 2021.83   213.5 2020.73   216.7 2020.32  226.842020.729   239.6 2025.35
   252.6 2026.66   268.9 2035.97     282 2042.18   337.4  2061.2   360.2 2072.23
   366.7 2076.17     383 2079.86   402.6 2088.09   422.1 2092.39   431.9 2096.45
#Mann= 5 ,-1 , 0
       0     .12       0  159.49    .016       0  200.95     .12       0
   213.5    .045       0  226.84     .12       0
Bank Sta=213.5,226.84
XS Rating Curve= 0 ,0
Exp/Cntr=0.3,0.1

Type RM Length L Ch R = 1 ,8663.2  ,258.4,244.1,229.5
XS GIS Cut Line= 3
     2049669.696      271807.288     2049562.925      271595.048
     2049353.289      271510.413
#Sta/Elev= 30
       0 2041.21      13 2035.55      26 2031.82    58.6 2028.26    91.1 2018.81
   110.7 2018.22  136.672013.367   143.2 2011.49   156.2 2010.86   166.9  2007.4
   175.8 2006.45  179.982007.369   188.8 2010.34   198.5 2011.36   214.8 2010.17
   221.3 2010.45   227.8  2011.6   237.6 2014.86   257.2 2024.23   276.9 2026.54
     290 2028.91     326 2040.62   365.4    2059   375.2 2065.33   378.5 2066.87
   388.3 2069.03   391.6 2070.42   401.4  2077.3   430.9 2091.48   463.7 2108.42
#Mann= 4 ,-1 , 0
       0     .12       0  136.67    .016       0   166.9    .045       0
  179.98     .12       0
Bank Sta=166.9,179.98
XS Rating Curve= 0 ,0
Exp/Cntr=0.3,0.1

Type RM Length L Ch R = 1 ,8419.1  ,230.6,231.8,230.1
XS GIS Cut Line= 2
     2049889.748      271541.663     2049534.279      271361.975
#Sta/Elev= 30
       0 2043.13    22.8 2029.37    45.7  2018.8    55.5    2016    81.6 2012.37
    84.9 2010.91    91.4 2005.18    97.9 2000.94  107.712000.122   114.3 2001.28
   130.6 2001.39  149.142002.984     160  2003.3     173 2002.15  185.68  1997.5
   189.4 1997.31   199.2 1997.46     209 1998.82  221.472004.101   235.1 2005.15
   244.9 2008.43  256.942014.208   267.7 2018.19   293.8 2021.18   329.7 2029.21
   342.8 2030.57   352.6 2034.52   368.9 2038.58   378.7 2042.39   398.3 2042.58
#Mann= 7 ,-1 , 0
       0     .12       0  107.71    .016       0  149.14     .12       0
  185.68    .045       0   199.2     .12       0  221.47    .016       0
  256.94     .12       0
Bank Sta=185.68,199.2
XS Rating Curve= 0 ,0
Exp/Cntr=0.3,0.1

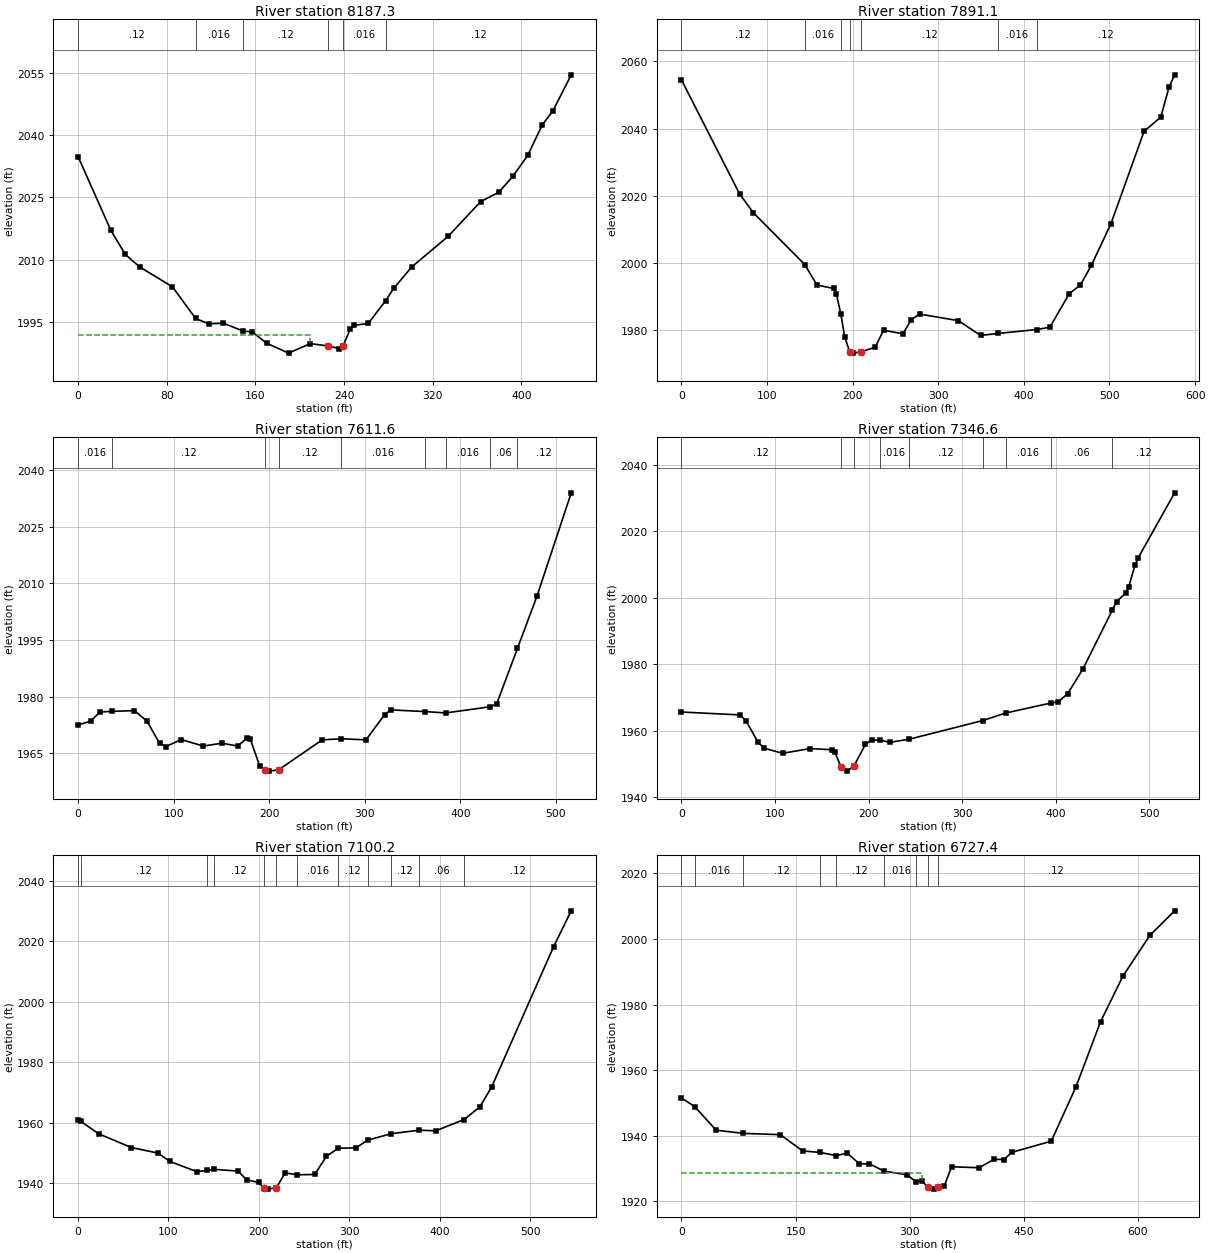
Type RM Length L Ch R = 1 ,8187.3  ,293.6,296.2,299.3
XS GIS Cut Line= 3
     2049961.362      271442.705     2049849.383      271265.621
     2049635.841      271166.663
#Sta/Elev= 30
       0 2034.85    29.5 2017.12    42.6 2011.27    55.6 2008.26    85.1 2003.48
  106.021995.848   117.8 1994.55     131 1994.71  149.021992.797   157.1 1992.61
   170.2 1989.87   189.9 1987.49   209.5 1989.78   225.9 1989.21   235.7 1988.58
   238.9 1989.13   245.5 1993.24   248.7 1994.17   261.8 1994.65  277.36 2000.09
   284.7 2003.08     301 2008.26   333.7  2015.6   363.2 2024.01   379.5 2026.24
   392.6 2030.22   405.6 2035.13   418.7 2042.46   428.5 2045.94   444.9 2054.56
#Mann= 6 ,-1 , 0
       0     .12       0  106.02    .016       0  149.02     .12       0
   225.9    .045       0   238.9    .016       0  277.36     .12       0
#XS Ineff= 2 , 0
          208.98 1991.76
Permanent Ineff=
       F       F
Bank Sta=225.9,238.9
XS Rating Curve= 0 ,0
Exp/Cntr=0.3,0.1

Type RM Length L Ch R = 1 ,7891.1  ,290.4,279.5,268.1
XS GIS Cut Line= 4
     2050184.019      271296.871     2050100.685      271151.038
     2049910.581       271027.34     2049729.591      271016.923
#Sta/Elev= 30
       0 2054.48    67.8 2020.57      84 2014.92  144.051999.489   158.3 1993.38
   177.7  1992.4   180.9  1990.8  186.23 1984.69   190.6 1978.04  196.441973.579
   200.4 1973.13   210.1 1973.55   226.3 1974.89     236 1979.94   258.7 1978.89
   268.4 1983.06   278.1 1984.75   323.5  1982.8   349.4  1978.4  369.79 1978.98
  415.191980.164   430.4 1980.84     453 1990.86     466  1993.4   478.9 1999.31
   501.6 2011.61   540.4 2039.17   559.9 2043.41   569.6 2052.36   576.1 2055.99
#Mann= 7 ,-1 , 0
       0     .12       0  144.05    .016       0  186.23     .12       0
  196.44    .045       0   210.1     .12       0  369.79    .016       0
  415.19     .12       0
Bank Sta=196.44,210.1
XS Rating Curve= 0 ,0
Exp/Cntr=0.3,0.1

Type RM Length L Ch R = 1 ,7611.6  ,254.1,265,275.6
XS GIS Cut Line= 3
     2050340.269      270880.205     2050049.904      270854.163
     2049858.498      270736.975
#Sta/Elev= 30
       0 1972.53    13.1 1973.51    22.9 1975.94   35.711976.128      59 1976.31
    72.1 1973.54    85.2 1967.68    91.7  1966.8   108.1 1968.64     131 1966.93
   150.7 1967.69   167.1 1966.92   176.9  1969.1   180.2 1968.75     190 1961.68
  195.731960.654   199.8 1960.29   209.8 1960.63   255.5 1968.58  275.361968.849
   301.3 1968.58   320.8 1975.27   327.3 1976.51  362.731976.065  384.521975.699
  430.511977.307   437.9 1978.03  459.711992.782   480.2 2006.66     516 2033.99
#Mann= 9 ,-1 , 0
       0    .016       0   35.71     .12       0  195.73    .045       0
   209.8     .12       0  275.36    .016       0  362.73     .12       0
  384.52    .016       0  430.51     .06       0  459.71     .12       0
Bank Sta=195.73,209.8
XS Rating Curve= 0 ,0
Exp/Cntr=0.3,0.1

Type RM Length L Ch R = 1 ,7346.6  ,249.6,246.4,243.3
XS GIS Cut Line= 3
     2050392.352      270720.048     2050098.081      270535.152
     2049919.696      270557.288
#Sta/Elev= 30
       0 1965.69    62.3 1964.83    68.8 1963.12      82 1956.56    88.5 1954.79
   108.2 1953.29   137.7 1954.71   160.6 1954.34   163.9 1953.66   170.5 1949.26
     177 1947.92  184.241949.372   196.7 1955.98   203.3 1957.24  211.891957.233
     223 1956.58  243.411957.511  322.251963.136  346.511965.383  394.611968.374
   403.1  1968.8   412.9  1971.2   429.2 1978.62  460.481996.222   465.2 1998.91
     475 2001.44   478.3 2003.42   484.8 2009.76   488.1 2011.94   527.3  2031.6
#Mann= 9 ,-1 , 0
       0     .12       0   170.5    .045       0  184.24     .12       0
  211.89    .016       0  243.41     .12       0  322.25     .06       0
  346.51    .016       0  394.61     .06       0  460.48     .12       0
Bank Sta=170.5,184.24
XS Rating Curve= 0 ,0
Exp/Cntr=0.3,0.1

Type RM Length L Ch R = 1 ,7100.2  ,361.1,372.8,379.2
XS GIS Cut Line= 3
     2050529.071      270522.132     2050402.769      270428.382
     2050048.602      270269.527
#Sta/Elev= 30
       0 1960.89    2.79 1960.45    22.9 1956.29      59 1951.76    88.5 1949.92
   101.6 1947.16   131.1 1943.82   143.1 1944.18  150.011944.566   176.9 1943.98
   186.6 1941.05   199.7 1940.24  205.111938.458   209.5 1938.02   219.3 1938.48
     229 1943.39  242.521942.754   261.7 1942.87   274.7 1948.88  287.711951.531
   307.3 1951.65  320.211954.189  346.311956.339  377.491957.501   395.4 1957.28
  426.891961.018   444.3 1965.18   457.4 1971.78   525.9 2018.14   545.4 2029.98
#Mann= 12 ,-1 , 0
       0    .016       0    2.79     .12       0   143.1     .06       0
  150.01     .12       0  205.11    .045       0   219.3     .12       0
  242.52    .016       0  287.71     .12       0  320.21    .016       0
  346.31     .12       0  377.49     .06       0  426.89     .12       0
Bank Sta=205.11,219.3
XS Rating Curve= 0 ,0
Exp/Cntr=0.3,0.1

Type RM Length L Ch R = 1 ,6727.4  ,357.7,366.8,376.1
XS GIS Cut Line= 4
     2050626.657      270423.468     2050560.685      270182.149
      2050411.38       270034.58     2050334.991      269862.705
#Sta/Elev= 30
       0 1951.51    17.51948.847    45.5 1941.68   81.45 1940.71     130 1940.32
   159.2 1935.37  182.671934.882  203.571933.925   217.7  1934.7   233.9 1931.43
   246.9 1931.43  266.231929.214   296.1  1928.1  308.021926.015   315.8 1926.22
  324.21 1924.22   332.2 1923.71  337.091924.219   345.3 1924.64   355.1 1930.53
   391.2 1930.23   410.9 1932.82     424 1932.72   433.9 1934.91     486 1938.33
   518.5  1954.9   550.9 1974.82   580.1 1988.61   615.8 2001.14   648.2 2008.58
#Mann= 9 ,-1 , 0
       0     .12       0    17.5    .016       0   81.45     .12       0
  182.67     .06       0  203.57     .12       0  266.23    .016       0
  308.02     .12       0  324.21    .045       0  337.09     .12       0
#XS Ineff= 2 , 0
          315.69 1928.61
Permanent Ineff=
       F       F
Bank Sta=324.21,337.09
XS Rating Curve= 0 ,0
Exp/Cntr=0.3,0.1

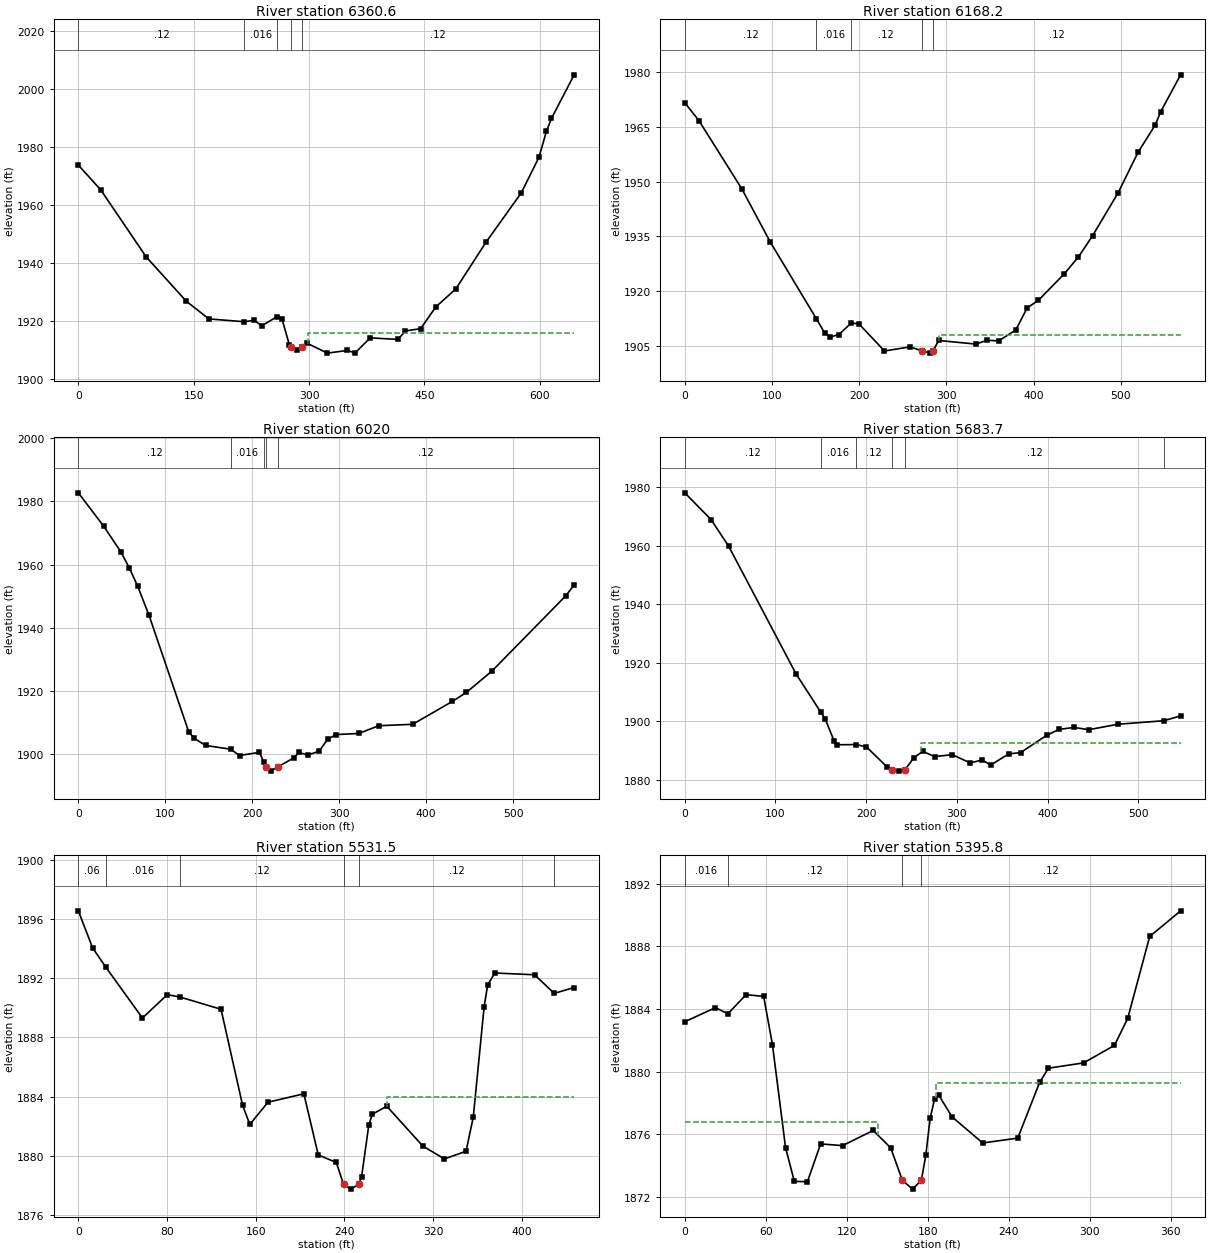
Type RM Length L Ch R = 1 ,6360.6  ,197.8,192.4,186.3
XS GIS Cut Line= 4
     2051038.116      270246.385      2050888.81      270124.857
     2050791.588      269906.107     2050633.602      269763.746
#Sta/Elev= 30
       0 1973.78    29.4 1965.13    88.1 1942.14   140.3 1926.84   169.7 1920.72
  216.021919.738   228.6 1920.28   238.4 1918.33  257.711921.404   264.7 1920.77
   274.5 1911.64  275.981911.089   284.3 1910.02   290.9 1910.99   297.4 1912.34
   323.7 1908.92   349.9 1909.85   359.8 1908.98   379.4 1914.18   415.5 1913.65
   425.3 1916.57     445 1917.36   464.6 1924.81   490.8 1931.07     530 1947.17
   575.8 1964.16   598.8 1976.41   608.6 1985.46   615.1 1989.87   644.6 2004.89
#Mann= 5 ,-1 , 0
       0     .12       0  216.02    .016       0  257.71     .12       0
  275.98    .045       0   290.9     .12       0
#XS Ineff= 2 , 0
                          299.07         1915.81
Permanent Ineff=
       F       F
Bank Sta=275.98,290.9
XS Rating Curve= 0 ,0
Exp/Cntr=0.3,0.1

Type RM Length L Ch R = 1 ,6168.2  ,143.8,148.3,151.6
XS GIS Cut Line= 3
     2051137.348      270107.566     2050888.867      269799.406
     2050751.063       269695.24
#Sta/Elev= 30
       0 1971.59    16.4 1966.62    65.4    1948    98.2 1933.36  150.841912.438
   160.3 1908.57   166.8 1907.45   176.7 1908.09   190.81911.242   199.6 1911.04
     229  1903.6   258.4 1904.72   271.5 1903.68   281.4 1903.01  284.761903.714
   291.2 1906.47   333.7 1905.49   346.8 1906.54   359.9 1906.35   379.5 1909.33
   392.6  1915.4   405.6 1917.49     435 1924.69   451.3 1929.31   467.6 1935.15
   496.9 1946.91   519.7 1957.98   539.3 1965.43   545.8 1969.16   568.6 1979.23
#Mann= 5 ,-1 , 0
       0     .12       0  150.84    .016       0   190.8     .12       0
   271.5    .045       0  284.76     .12       0
#XS Ineff= 2 , 0
                          291.64         1908.11
Permanent Ineff=
       F       F
Bank Sta=271.5,284.76
XS Rating Curve= 0 ,0
Exp/Cntr=0.3,0.1

Type RM Length L Ch R = 1 ,6020    ,340.7,336.2,331.4
XS GIS Cut Line= 4
     2051248.185      270022.427     2051124.921      269897.427
      2051045.06      269755.066      2050857.56      269619.649
#Sta/Elev= 30
       0 1982.72    29.3 1972.09    48.8 1964.04    58.5 1959.02    68.3 1953.07
    81.3  1943.9   126.8 1907.07   133.3 1904.89   146.3 1902.64  175.09 1901.46
   185.4 1899.46   208.2 1900.46  213.371897.288  215.371895.932   221.3 1894.51
   229.81895.916   247.4 1898.66   253.9 1900.42   263.7 1899.59   276.8 1900.82
   286.6 1904.57   296.3  1906.1   322.5 1906.44   345.3  1908.9   384.4 1909.35
     430 1916.59   446.3 1919.48   475.6 1926.24   560.3 1950.03   570.1 1953.51
#Mann= 5 ,-1 , 0
       0     .12       0  175.09    .016       0  213.37     .12       0
  215.37    .045       0   229.8     .12       0
Bank Sta=215.37,229.8
XS Rating Curve= 0 ,0
Exp/Cntr=0.3,0.1

Type RM Length L Ch R = 1 ,5683.7  ,151.6,152.3,152.7
XS GIS Cut Line= 3
     2051406.171      269946.038      2051442.63      269772.427
      2051201.31      269492.913
#Sta/Elev= 30
       0 1978.15      29 1968.97    48.4 1959.86   122.6 1916.21  149.791903.135
   154.8 1900.75   164.5 1893.33   167.7 1891.93  189.131891.987   200.3 1891.18
   223.2 1884.27  228.861883.386   236.2  1882.9   242.8 1883.37   252.6 1887.51
   262.4 1889.66   275.4 1887.88     295 1888.52   314.6 1885.72   327.7 1886.69
   337.5    1885   357.1  1888.8   370.2 1889.24   399.6 1895.27   412.7 1897.18
     429 1897.85   445.4  1897.1     478 1898.95  528.11 1900.15   546.7  1901.8
#Mann= 6 ,-1 , 0
       0     .12       0  149.79    .016       0  189.13     .12       0
  228.86    .045       0   242.8     .12       0  528.11     .06       0
#XS Ineff= 2 , 0
                          260.68         1892.67
Permanent Ineff=
       F       F
Bank Sta=228.86,242.8
XS Rating Curve= 0 ,0
Exp/Cntr=0.3,0.1

Type RM Length L Ch R = 1 ,5531.5  ,133.3,135.6,137.6
XS GIS Cut Line= 3
     2051529.058      269809.172     2051579.855      269712.515
     2051365.657      269451.005
#Sta/Elev= 30
       0 1896.55    12.8 1894.06   24.83 1892.74    57.8 1889.31    80.3 1890.89
    92.11890.718   128.7  1889.9   148.2  1883.4   154.7 1882.12     171 1883.62
   203.4 1884.19   216.4 1880.06   232.7 1879.55   239.2 1878.07   245.7 1877.75
  252.871878.072   255.5 1878.59     262 1882.09   265.2 1882.81   278.2 1883.35
   310.7 1880.66   330.2 1879.79   349.7 1880.31   356.2 1882.61     366 1890.07
   369.2 1891.55   375.7 1892.35   411.5 1892.23  429.231890.974   447.2 1891.37
#Mann= 6 ,-1 , 0
       0     .06       0   24.83    .016       0    92.1     .12       0
   239.2    .045       0  252.87     .12       0  429.23     .06       0
#XS Ineff= 2 , 0
                          278.64         1883.95
Permanent Ineff=
       F       F
Bank Sta=239.2,252.87
XS Rating Curve= 0 ,0
Exp/Cntr=0.3,0.1

Type RM Length L Ch R = 1 ,5395.8  ,220.5,221.8,222
XS GIS Cut Line= 3
     2051697.243      269668.113     2051539.908      269433.738
     2051463.954      269395.761
#Sta/Elev= 30
       0 1883.19    22.7 1884.09    31.9  1883.7    45.4 1884.92    58.4 1884.81
    64.9 1881.73    74.6 1875.15    81.1 1872.99    90.8 1872.96   100.6 1875.38
   116.8 1875.27   139.5 1876.24   152.5 1875.13   161.11873.057   168.7 1872.49
   175.2 1873.06   178.5 1874.66   181.7 1877.02     185 1878.26   188.2 1878.48
   197.9 1877.11   220.6 1875.44   246.6 1875.75   262.8 1879.32   269.3 1880.22
   295.4 1880.56   318.2 1881.68     328  1883.4   344.3 1888.64   367.2 1890.28
#Mann= 4 ,-1 , 0
       0    .016       0    31.9     .12       0   161.1    .045       0
   175.2     .12       0
#XS Ineff= 2 , 0
          142.83 1876.76  186.17         1879.25
Permanent Ineff=
       F       F
Bank Sta=161.1,175.2
XS Rating Curve= 0 ,0
Exp/Cntr=0.3,0.1

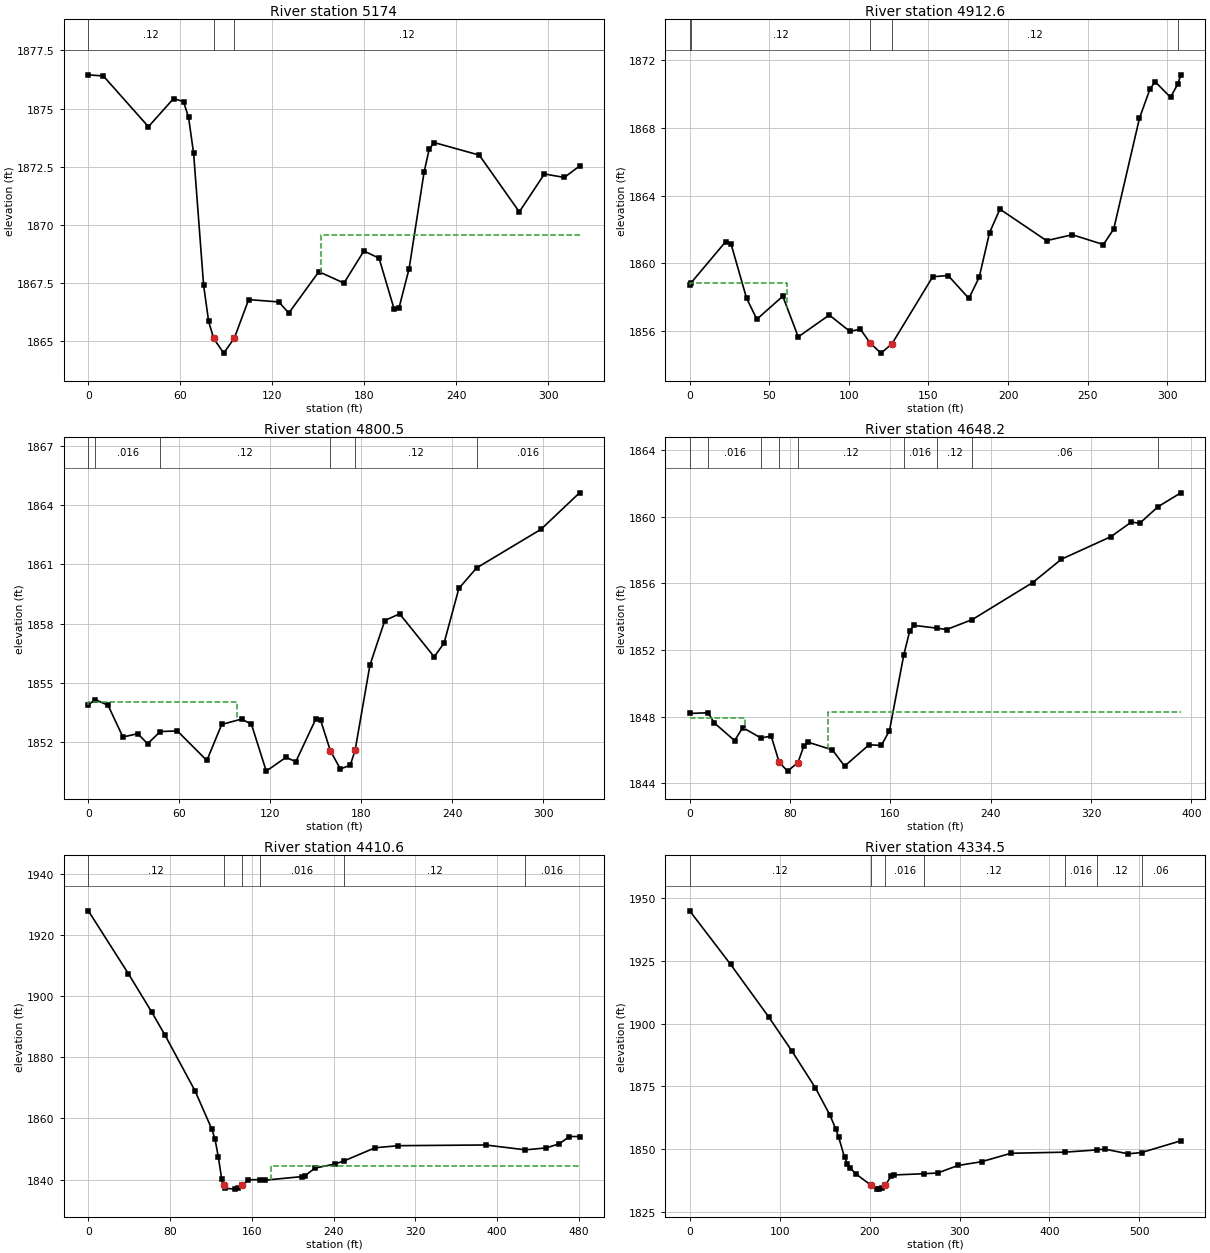
Type RM Length L Ch R = 1 ,5174    ,257,261.4,264.7
XS GIS Cut Line= 2
     2051848.068      269584.563     2051686.393       269307.87
#Sta/Elev= 30
       0 1876.45     9.8  1876.4    39.2 1874.22    55.6 1875.43    62.1  1875.3
    65.4 1874.62    68.7 1873.07    75.2 1867.41    78.5 1865.85    81.8 1865.12
    88.3 1864.49   95.21 1865.13   104.6 1866.79   124.3 1866.69   130.8 1866.21
   150.4 1867.99   166.8  1867.5   179.8 1868.88   189.7 1868.57   199.5 1866.39
   202.7 1866.43   209.3 1868.12   219.1 1872.28   222.4 1873.25   225.6 1873.54
   255.1    1873   281.2 1870.56   297.6 1872.19   310.6 1872.04   320.5 1872.53
#Mann= 3 ,-1 , 0
       0     .12       0    81.8    .045       0   95.21     .12       0
#XS Ineff= 2 , 0
                           151.7         1869.58
Permanent Ineff=
       F       F
Bank Sta=81.8,95.21
XS Rating Curve= 0 ,0
Exp/Cntr=0.3,0.1

Type RM Length L Ch R = 1 ,4912.6  ,109.5,112.1,113.7
XS GIS Cut Line= 2
     2052056.401      269503.183     2051950.065      269213.469
#Sta/Elev= 30
       0  1858.7     .551858.815    22.7 1861.29      26 1861.14    35.7 1857.95
    42.2  1856.7    58.5 1858.06    68.2 1855.66    87.7 1856.95   100.7 1855.98
   107.2 1856.12  113.41 1855.29   120.2  1854.7   127.1 1855.25   152.7 1859.21
   162.4 1859.28   175.4 1857.93   181.9 1859.18   188.4 1861.81   194.9  1863.2
   224.2 1861.34   240.4 1861.69   259.9 1861.11   266.4 1862.02   282.6 1868.57
   289.1 1870.27   292.4 1870.73   302.1  1869.8  306.611870.577   308.6 1871.13
#Mann= 5 ,-1 , 0
       0    .016       0     .55     .12       0  113.41    .045       0
   127.1     .12       0  306.61    .016       0
#XS Ineff= 2 , 0
            61.4 1858.86
Permanent Ineff=
       F       F
Bank Sta=113.41,127.1
XS Rating Curve= 0 ,0
Exp/Cntr=0.3,0.1

Type RM Length L Ch R = 1 ,4800.5  ,149.9,152.3,153.7
XS GIS Cut Line= 3
     2052139.044      269481.592      2052070.41      269233.365
     2052012.071      269201.336
#Sta/Elev= 30
       0 1853.88    4.591854.136      13 1853.85    22.8 1852.24    32.6 1852.41
    39.1  1851.9   47.481852.518    58.7 1852.55    78.2 1851.05      88 1852.88
   101.1 1853.15   107.6 1852.89   117.4 1850.51   130.4 1851.21   136.9 1850.99
     150 1853.14   153.2 1853.11   159.7 1851.54   166.3 1850.62   172.8 1850.81
     176 1851.56   185.8 1855.89   195.6 1858.15   205.4 1858.49   228.2 1856.31
   234.7    1857   244.5 1859.78  256.161860.818   298.7 1862.78   324.1 1864.63
#Mann= 6 ,-1 , 0
       0     .12       0    4.59    .016       0   47.48     .12       0
   159.7    .045       0     176     .12       0  256.16    .016       0
#XS Ineff= 2 , 0
           97.88    1854
Permanent Ineff=
       F       F
Bank Sta=159.7,176
XS Rating Curve= 0 ,0
Exp/Cntr=0.3,0.1

Type RM Length L Ch R = 1 ,4648.2  ,260.4,237.6,213.3
XS GIS Cut Line= 3
     2052253.884      269420.717     2052211.566      269200.448
     2052044.466      269192.853
#Sta/Elev= 30
       0  1848.2   14.761848.239    19.5 1847.64    35.8 1846.57    42.3 1847.35
   56.831846.729      65 1846.84    71.3 1845.28      78 1844.74    86.3 1845.25
      91 1846.24    94.3 1846.48   113.8 1846.01   123.5 1845.04     143 1846.32
   152.8 1846.28   159.3 1847.17  170.731851.724   175.5 1853.16   178.8 1853.48
  197.221853.314   204.8 1853.23   225.41853.833   273.5 1856.05   296.4 1857.45
   335.8  1858.8   352.2 1859.68   358.8  1859.6  373.24 1860.59   391.6 1861.43
#Mann= 9 ,-1 , 0
       0     .12       0   14.76    .016       0   56.83     .12       0
    71.3    .045       0    86.3     .12       0  170.73    .016       0
  197.22     .12       0   225.4     .06       0  373.24     .12       0
#XS Ineff= 2 , 0
           43.76 1847.95  110.22         1848.29
Permanent Ineff=
       F       F
Bank Sta=71.3,86.3
XS Rating Curve= 0 ,0
Exp/Cntr=0.3,0.1

Type RM Length L Ch R = 1 ,4410.6  ,90.1,76.1,61.1
XS GIS Cut Line= 3
     2052551.883      269293.712     2052279.314      269184.337
     2052182.091      269024.614
#Sta/Elev= 30
       0 1927.81    39.2 1907.26      62 1894.76    75.1 1887.15   104.4 1869.01
   120.7 1856.62     124 1853.18   127.3 1847.25   130.5 1840.17  132.64 1838.29
   133.8 1837.19   143.6  1836.9   146.8 1837.12   150.6 1838.18   156.6 1839.95
  167.551839.992     173 1839.83   208.8 1840.98   212.1 1841.32   221.9 1843.78
   241.5 1845.11  250.661846.177   280.6 1850.41   303.5 1851.09   388.8 1851.32
   427.81849.731   447.9 1850.36     461 1851.71   470.8 1854.09   480.7 1854.07
#Mann= 6 ,-1 , 0
       0     .12       0  132.64    .045       0   150.6     .12       0
  167.55    .016       0  250.66     .12       0   427.8    .016       0
#XS Ineff= 2 , 0
                          178.53         1844.53
Permanent Ineff=
       F       F
Bank Sta=132.64,150.6
XS Rating Curve= 0 ,0
Exp/Cntr=0.3,0.1

Type RM Length L Ch R = 1 ,4334.5  ,56.9,56.9,57.4
XS GIS Cut Line= 4
     2052616.241      269260.274     2052468.671       269159.58
     2052371.449      269183.885     2052197.838       268980.76
#Sta/Elev= 30
       0 1945.02    45.5 1923.64    87.7 1902.75   113.7 1889.04   139.7 1874.41
   155.9 1863.53   162.4 1857.98   165.7 1854.62   172.2 1846.64   175.4 1844.16
   178.6 1842.28   185.1 1839.95   201.3 1835.61   207.8 1834.08     211 1833.97
   214.2 1834.32   217.6 1835.61   223.9 1839.08   227.1 1839.63  260.131840.108
   275.6 1840.41   298.4 1843.41   324.5 1844.91   357.1 1848.27   417.11848.723
  453.111849.623   461.4 1849.95   487.4 1848.06  502.43 1848.57   546.1 1853.26
#Mann= 7 ,-1 , 0
       0     .12       0   201.3    .045       0   217.6    .016       0
  260.13     .12       0   417.1    .016       0  453.11     .12       0
  502.43     .06       0
Bank Sta=201.3,217.6
XS Rating Curve= 0 ,0
Exp/Cntr=0.3,0.1