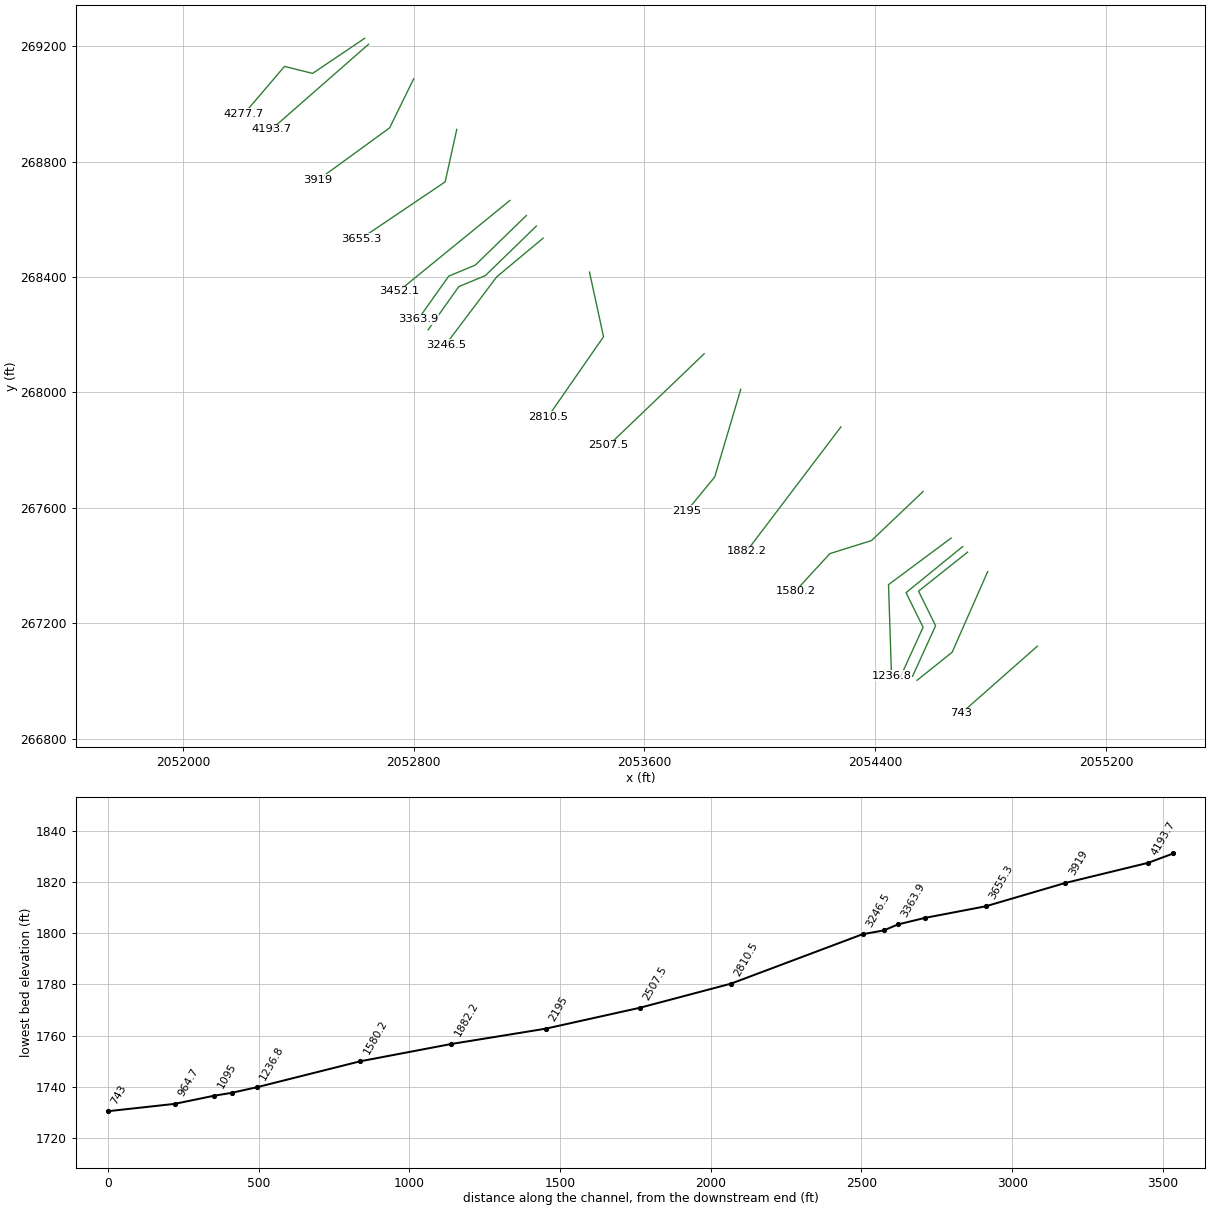
HEC-RAS study GRFTHCK.prj: GRFTHCK

--- GRFTHCK.g01 (geometry) --- (continued)

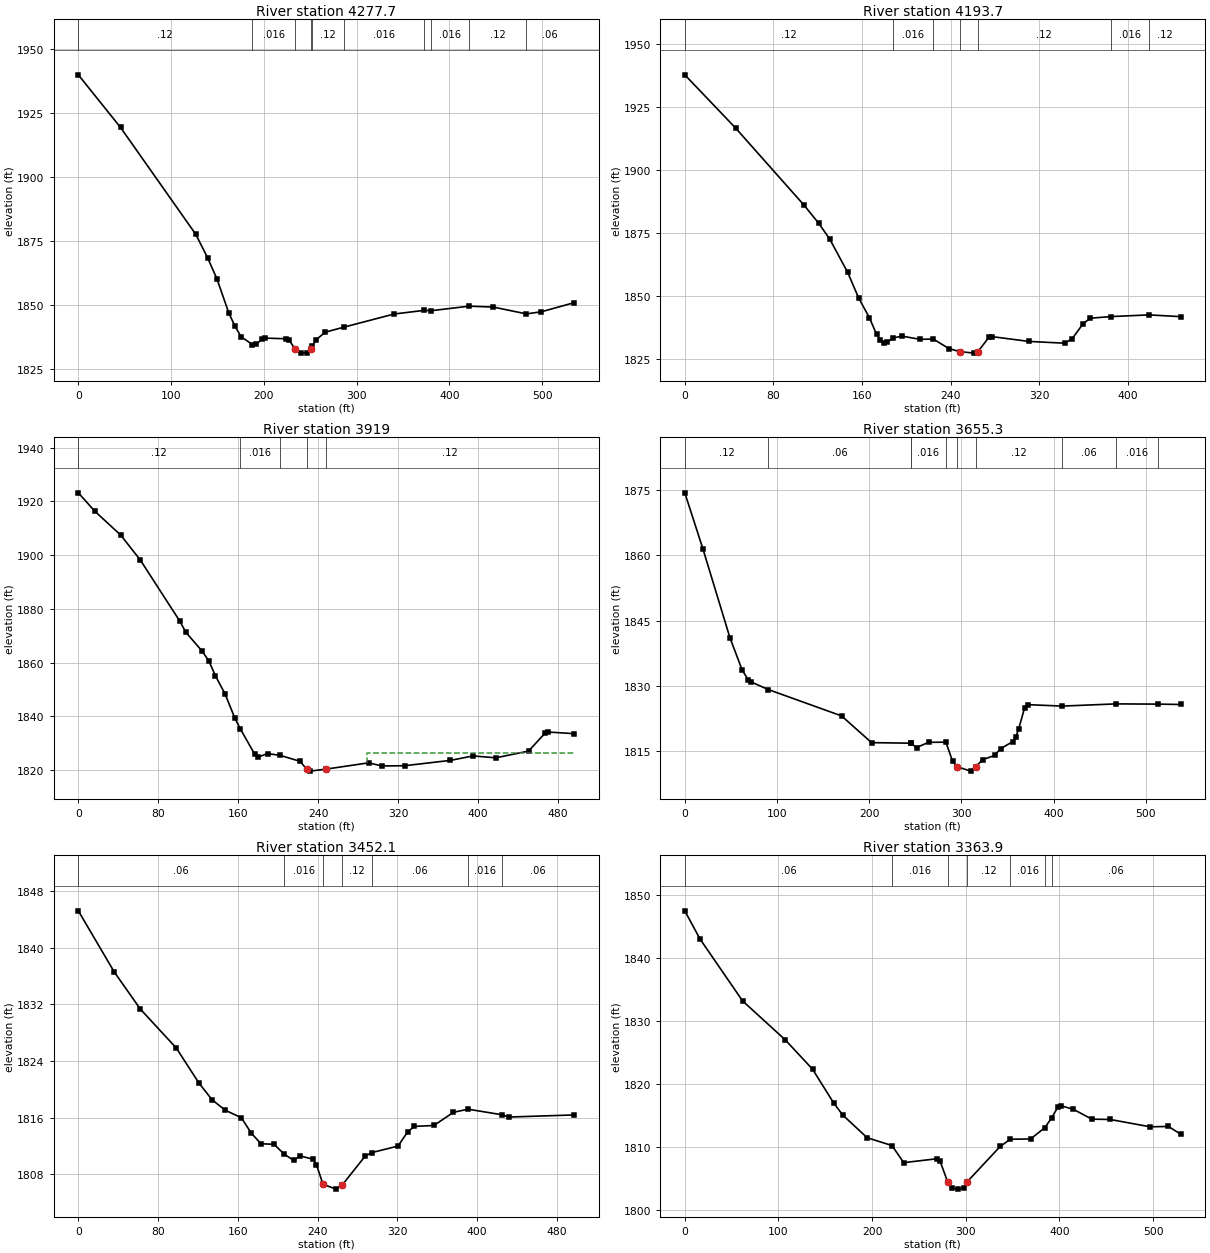
Type RM Length L Ch R = 1 ,4277.7  ,61.9,84,105.6
XS GIS Cut Line= 4
      2052630.13      269227.288     2052449.574       269105.76
     2052352.352      269130.066     2052211.727      268965.135
#Sta/Elev= 30
       0 1939.94    45.5 1919.36   126.7 1877.52   139.7 1868.14   149.4 1860.17
   162.4 1846.64   168.9 1841.66   175.4 1837.56   187.6 1834.46   191.7  1834.5
   198.2 1836.64   201.4 1836.97   224.1 1836.71   227.3 1836.16   233.8 1832.68
   240.3  1831.1   246.7  1831.2  250.45 1832.68  252.021833.748   256.4 1836.33
   266.1 1839.27  286.271841.259   340.5  1846.4  373.221847.835  380.261847.677
   421.21849.458   447.3 1849.12  483.081846.448     499 1847.25   534.6 1850.83
#Mann= 10 ,-1 , 0
       0     .12       0   187.6    .016       0   233.8    .045       0
  250.45    .016       0  252.02     .12       0  286.27    .016       0
  373.22     .12       0  380.26    .016       0   421.2     .12       0
  483.08     .06       0
Bank Sta=233.8,250.45
XS Rating Curve= 0 ,0
Exp/Cntr=0.3,0.1

Type RM Length L Ch R = 1 ,4193.7  ,276.2,274.7,272.5
XS GIS Cut Line= 2
     2052643.897      269206.906     2052307.091      268911.767
#Sta/Elev= 30
       0 1937.71    45.8 1916.66   107.9 1885.95   120.9  1878.9   130.8 1872.68
   147.1 1859.43   156.9 1849.38   166.7 1841.47   173.2 1834.87   176.5 1832.68
   179.8 1831.57     183 1831.69  187.691833.379   196.1 1834.16   212.5 1832.88
  224.331833.006   238.6 1829.22   248.4    1828   261.5 1827.42   264.8    1828
   274.6 1833.69   277.8 1833.94   310.5 1832.07   343.2 1831.35   349.8 1833.11
   359.6    1839   366.1 1841.25  384.641841.896   419.2 1842.57   447.8 1841.88
#Mann= 7 ,-1 , 0
       0     .12       0  187.69    .016       0  224.33     .12       0
   248.4    .045       0   264.8     .12       0  384.64    .016       0
   419.2     .12       0
Bank Sta=248.4,264.8
XS Rating Curve= 0 ,0
Exp/Cntr=0.3,0.1

Type RM Length L Ch R = 1 ,3919    ,264.3,263.7,262.6
XS GIS Cut Line= 3
     2052800.147      269087.114     2052716.814      268916.975
      2052468.55       268736.42
#Sta/Elev= 30
       0 1923.21    16.3 1916.43    42.5 1907.44    62.1 1898.16   101.3 1875.59
   107.8 1871.21   124.1 1864.17   130.7 1860.58   137.2  1855.1     147 1848.23
   156.8 1839.18  162.161835.314   176.4 1825.97   179.6 1824.72   189.4 1826.09
  202.141825.422   222.1  1823.2   228.6 1820.26   231.9 1819.56   248.2 1820.32
   290.7 1822.65   303.8 1821.49   326.6 1821.57   372.3 1823.55   395.2 1825.22
     418 1824.52   450.7 1827.02     467 1833.58   470.3 1834.12   496.4 1833.51
#Mann= 5 ,-1 , 0
       0     .12       0  162.16    .016       0  202.14     .12       0
   228.6    .045       0   248.2     .12       0
#XS Ineff= 2 , 0
                          289.47         1826.25
Permanent Ineff=
       F       F
Bank Sta=228.6,248.2
XS Rating Curve= 0 ,0
Exp/Cntr=0.3,0.1

Type RM Length L Ch R = 1 ,3655.3  ,200.8,203.2,204.9
XS GIS Cut Line= 3
     2052949.453      268911.767     2052909.264      268729.858
     2052617.855      268533.295
#Sta/Elev= 30
       0 1874.35    19.6 1861.52      49 1841.06    62.1 1833.73    68.6 1831.48
    71.9 1830.93   90.631829.181     170 1823.14   202.6    1817  245.071816.876
  245.351816.837   251.4 1815.88   264.4 1817.07  283.181817.111   290.4 1812.76
   295.1  1811.5     310 1810.46  315.56 1811.45     323  1813.1     336 1814.05
   342.5 1815.62   355.5  1817.2   358.8 1818.19     362 1820.05   368.6 1825.02
   371.8 1825.72  409.621825.389  467.551825.897  513.211825.843   537.8 1825.76
#Mann= 10 ,-1 , 0
       0     .12       0   90.63     .06       0  245.07     .12       0
  245.35    .016       0  283.18     .12       0   295.1    .045       0
  315.56     .12       0  409.62     .06       0  467.55    .016       0
  513.21     .06       0
Bank Sta=295.1,315.56
XS Rating Curve= 0 ,0
Exp/Cntr=0.3,0.1

Type RM Length L Ch R = 1 ,3452.1  ,94.4,88.2,81.3
XS GIS Cut Line= 2
      2053133.48      268665.239     2052748.064      268351.003
#Sta/Elev= 30
       0  1845.2      36 1836.57    62.2 1831.32    98.2 1825.83     121 1820.87
   134.1 1818.52   147.2 1817.05   163.6 1815.96   173.4 1813.81   183.2  1812.3
   196.3 1812.22  206.341810.854   215.9 1809.95   222.5 1810.59   235.6  1810.1
   238.8 1809.35   245.4 1806.57   258.5 1805.89   264.6 1806.46   287.9 1810.59
  294.711811.063   320.6 1811.97   330.4 1813.99     337 1814.75   356.6 1814.88
   376.2 1816.74  390.931817.181  425.071816.389   431.8 1816.07   497.3 1816.37
#Mann= 7 ,-1 , 0
       0     .06       0  206.34    .016       0   245.4    .045       0
   264.6     .12       0  294.71     .06       0  390.93    .016       0
  425.07     .06       0
Bank Sta=245.4,264.6
XS Rating Curve= 0 ,0
Exp/Cntr=0.3,0.1

Type RM Length L Ch R = 1 ,3363.9  ,47.1,47,47
XS GIS Cut Line= 4
     2053190.772      268613.156     2053013.689      268441.281
     2052921.675      268403.087     2052815.772      268253.781
#Sta/Elev= 30
       0 1847.51    16.2 1843.05    61.7 1833.22   107.2 1827.05   136.4 1822.39
   159.1    1817   168.8 1815.09   194.8 1811.51   221.21810.277   233.8 1807.56
   269.3 1808.18   272.5 1807.85   280.7 1804.51   285.3 1803.52   291.8 1803.36
   298.2 1803.56   301.4  1804.5   336.8 1810.13  347.661811.275   369.3 1811.32
  384.421813.099  391.931814.708   398.7 1816.45     402 1816.57     415 1816.02
   434.7 1814.46   454.3 1814.41   496.8 1813.25   516.4  1813.3   529.5 1812.09
#Mann= 7 ,-1 , 0
       0     .06       0   221.2    .016       0   280.7    .045       0
   301.4     .12       0  347.66    .016       0  384.42     .12       0
  391.93     .06       0
Bank Sta=280.7,301.4
XS Rating Curve= 0 ,0
Exp/Cntr=0.3,0.1

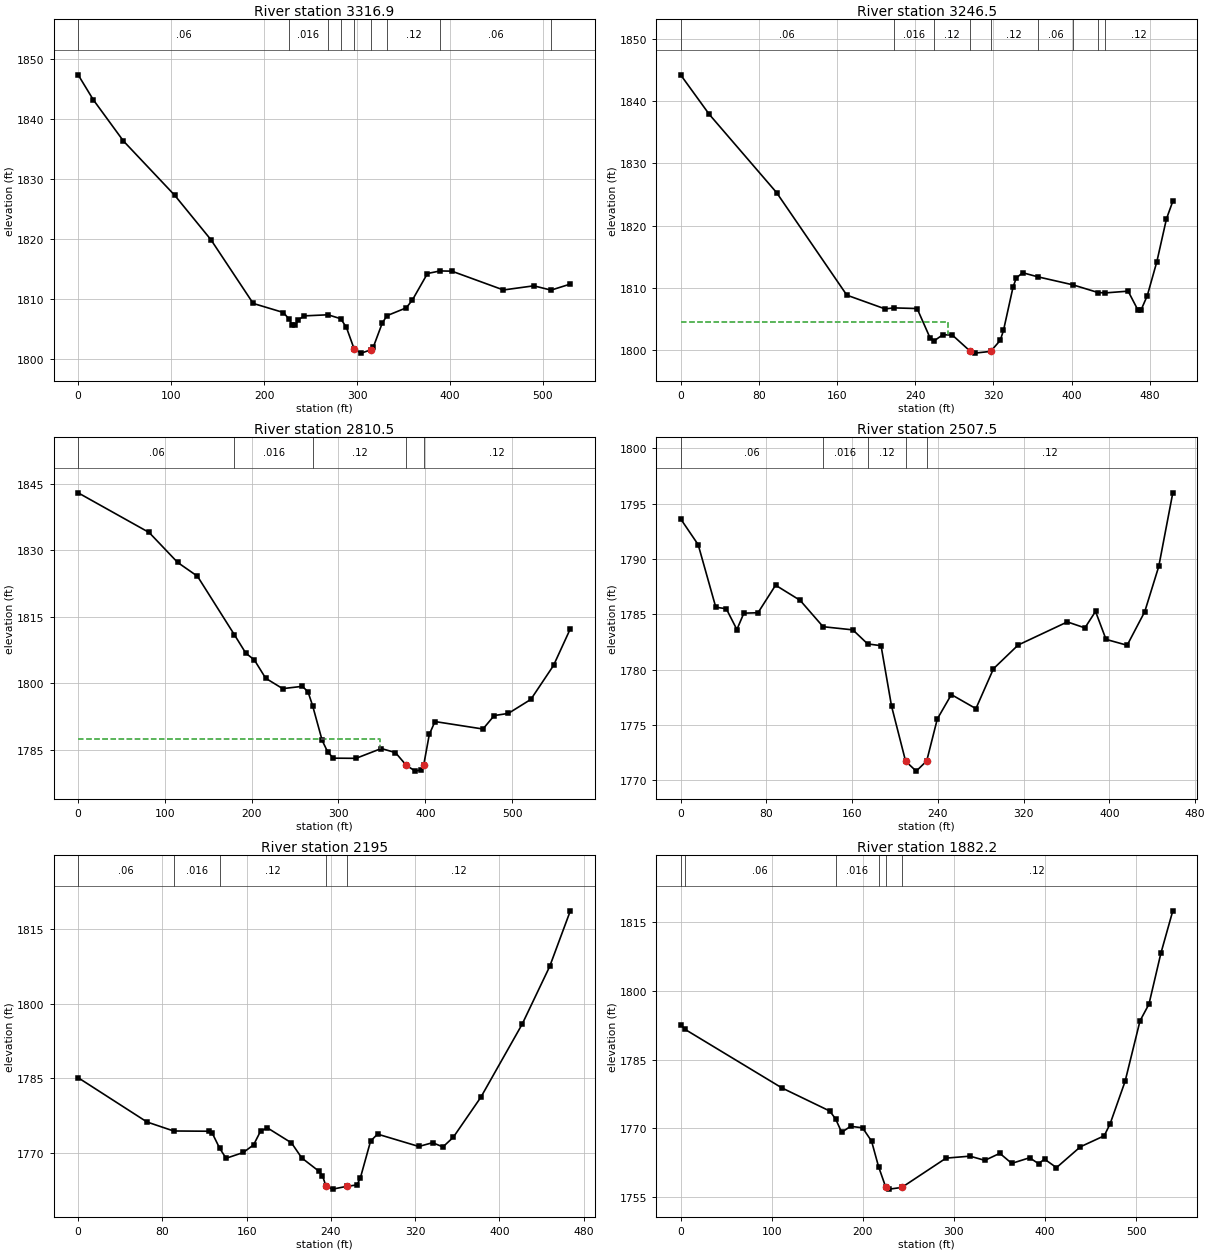
Type RM Length L Ch R = 1 ,3316.9  ,58.2,70.4,82.2
XS GIS Cut Line= 4
     2053225.494      268576.698     2053048.411      268404.823
     2052956.397      268366.628     2052850.494      268217.323
#Sta/Elev= 30
       0 1847.35    16.2 1843.22    48.7 1836.34   103.9  1827.3   142.9  1819.9
   188.3 1809.31   220.8  1807.8  226.441806.776   230.5 1805.73   233.8 1805.76
     237 1806.62   243.5 1807.24  268.81 1807.42  282.471806.767   288.6 1805.32
  297.04 1801.68   304.6 1801.04   315.3 1801.62   317.5 1802.03   327.1 1806.02
  332.181807.269   352.9 1808.57   359.5 1809.86   375.8 1814.29  389.291814.716
     402 1814.68   457.5 1811.55   490.2 1812.24  508.741811.524   529.5 1812.53
#Mann= 9 ,-1 , 0
       0     .06       0  226.44    .016       0  268.81     .06       0
  282.47    .016       0  297.04    .045       0   315.3    .016       0
  332.18     .12       0  389.29     .06       0  508.74     .12       0
Bank Sta=297.04,315.3
XS Rating Curve= 0 ,0
Exp/Cntr=0.3,0.1

Type RM Length L Ch R = 1 ,3246.5  ,434.7,436,436.5
XS GIS Cut Line= 3
     2053248.633      268534.439     2053087.913      268400.453
     2052910.884      268165.507
#Sta/Elev= 30
       0 1844.18    29.4 1837.82    98.1  1825.3     170 1808.84   209.2 1806.63
  217.951806.798   241.9 1806.69     255 1802.03  259.061801.485   268.1 1802.48
   277.9 1802.44   296.3 1799.83   300.8 1799.54   317.1 1799.82   326.9 1801.59
   330.2 1803.17     340 1810.13   343.3 1811.59   349.8 1812.44  365.251811.783
  401.271810.493  426.881809.261  434.491809.202   457.7 1809.48   467.5 1806.52
   470.7 1806.38   477.3 1808.76   487.1 1814.22   496.9 1821.07   503.4  1823.9
#Mann= 9 ,-1 , 0
       0     .06       0  217.95    .016       0  259.06     .12       0
   296.3    .045       0   317.1     .12       0  365.25     .06       0
  401.27     .12       0  426.88     .06       0  434.49     .12       0
#XS Ineff= 2 , 0
          273.68 1804.59
Permanent Ineff=
       F       F
Bank Sta=296.3,317.1
XS Rating Curve= 0 ,0
Exp/Cntr=0.3,0.1

Type RM Length L Ch R = 1 ,2810.5  ,307,303,297.9
XS GIS Cut Line= 3
     2053409.522      268416.975     2053458.133      268193.017
     2053265.425      267915.239
#Sta/Elev= 30
       0 1842.91    81.8 1833.98   114.6 1827.25   137.5 1824.13  180.151810.933
   193.2 1806.82     203 1805.31   216.1 1801.17   235.7 1798.83   258.4 1799.35
   264.9 1798.11  270.261794.949   281.2 1787.17   287.7 1784.53   294.2 1783.18
   320.2 1783.14   349.4 1785.35   365.7 1784.42   378.1 1781.58   388.5 1780.26
     395 1780.55   398.2 1781.62   404.7 1788.54   411.2 1791.42   466.5 1789.74
   479.5 1792.77   495.7 1793.25   521.7 1796.41   547.8 1804.04   567.2 1812.31
#Mann= 5 ,-1 , 0
       0     .06       0  180.15    .016       0  270.26     .12       0
   378.1    .045       0   398.2     .12       0
#XS Ineff= 2 , 0
          347.99 1787.45
Permanent Ineff=
       F       F
Bank Sta=378.1,398.2
XS Rating Curve= 0 ,0
Exp/Cntr=0.3,0.1

Type RM Length L Ch R = 1 ,2507.5  ,300.2,312.6,324
XS GIS Cut Line= 2
     2053807.091      268133.989     2053475.494      267816.281
#Sta/Elev= 30
       0 1793.63    16.4 1791.29    32.8 1785.64    42.6  1785.5    52.5 1783.62
      59  1785.1    72.2 1785.14    88.6 1787.63   111.5 1786.26  132.921783.876
   160.7 1783.59  174.481782.322     187 1782.16   196.8 1776.69   209.9 1771.72
   219.8 1770.82   229.6 1771.74   239.5 1775.54   252.6 1777.74   275.5 1776.47
   291.9 1780.08   314.9 1782.22   360.8 1784.31   377.2 1783.77   387.1 1785.26
   396.9 1782.73   416.6  1782.2     433 1785.23   446.1 1789.33   459.2 1795.98
#Mann= 5 ,-1 , 0
       0     .06       0  132.92    .016       0  174.48     .12       0
   209.9    .045       0   229.6     .12       0
Bank Sta=209.9,229.6
XS Rating Curve= 0 ,0
Exp/Cntr=0.3,0.1

Type RM Length L Ch R = 1 ,2195    ,320.7,312.8,304.6
XS GIS Cut Line= 3
     2053933.828      268010.725      2053843.55      267706.906
     2053748.064      267590.587
#Sta/Elev= 30
       0 1785.09    65.4 1776.17   90.67 1774.36   124.2 1774.31   127.4  1773.9
  134.451770.851   140.5 1768.86   156.8 1770.03   166.6 1771.56   173.2 1774.32
   179.7 1774.99   202.6 1771.96   212.4 1768.92   228.7 1766.25     232 1765.37
   235.3 1763.28   241.8 1762.65   254.9 1763.21   264.7 1763.49   267.9 1764.83
   277.7 1772.32   284.3 1773.73   323.5 1771.24   336.6    1772   346.4 1771.15
   356.2 1773.08   382.4 1781.15   421.6 1795.85   447.8  1807.5   467.4  1818.7
#Mann= 5 ,-1 , 0
       0     .06       0   90.67    .016       0  134.45     .12       0
   235.3    .045       0   254.9     .12       0
Bank Sta=235.3,254.9
XS Rating Curve= 0 ,0
Exp/Cntr=0.3,0.1

Type RM Length L Ch R = 1 ,1882.2  ,315.9,301.9,287.8
XS GIS Cut Line= 2
      2054281.05      267880.517     2053954.661      267449.962
#Sta/Elev= 30
       0 1792.64     4.81791.623   111.3  1778.8   163.7 1773.76  170.141772.032
   176.8  1769.1   186.6 1770.42   199.7 1770.09   209.6 1767.18  217.281761.605
  225.22 1757.08   229.2 1756.68   242.8 1757.05   291.4 1763.46   317.6 1763.89
     334 1762.97   350.4 1764.51   363.5 1762.31   383.1 1763.54   392.9 1762.25
   399.5 1763.24   412.6 1761.38   438.8 1765.93     465 1768.34   471.5 1770.97
   487.9 1780.23   504.3 1793.48   514.1 1797.12   527.2 1808.25   540.3 1817.54
#Mann= 6 ,-1 , 0
       0    .016       0     4.8     .06       0  170.14    .016       0
  217.28     .12       0  225.22    .045       0   242.8     .12       0
Bank Sta=225.22,242.8
XS Rating Curve= 0 ,0
Exp/Cntr=0.3,0.1

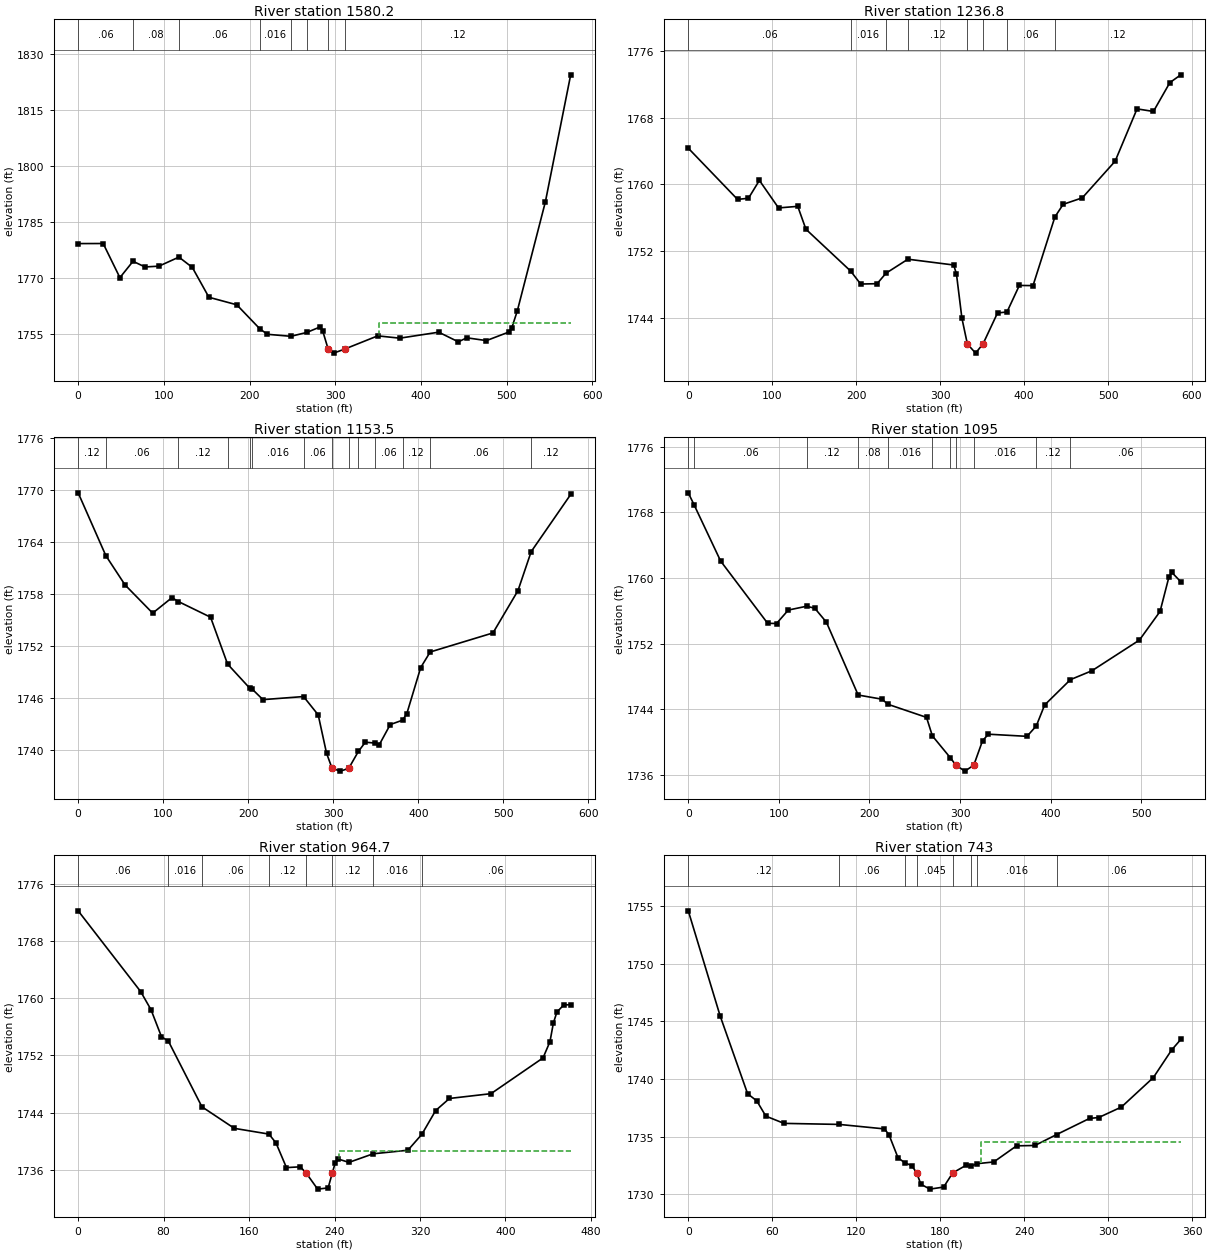
Type RM Length L Ch R = 1 ,1580.2  ,313.5,343.5,371.8
XS GIS Cut Line= 4
     2054565.772      267656.559     2054386.953       267486.42
     2054242.855      267441.281     2054123.064      267311.073
#Sta/Elev= 30
       0 1779.23    29.2 1779.25    48.7 1770.12   64.011774.492      78 1772.98
    94.2 1773.19  117.591775.613   133.2 1772.86   152.6 1764.87   185.1 1762.86
  211.991756.438   220.8 1754.97  248.261754.427  266.911755.472   282.2 1756.92
   285.4 1755.87   291.7 1751.05   298.2 1749.93   311.1 1751.02   349.6 1754.55
   375.3 1753.93   420.8 1755.53   443.7 1752.95   453.5 1754.03   476.5 1753.28
   502.7 1755.58     506 1756.65   512.5 1761.22   545.3 1790.43   574.8 1824.37
#Mann= 8 ,-1 , 0
       0     .06       0   64.01     .08       0  117.59     .06       0
  211.99    .016       0  248.26     .08       0  266.91     .06       0
   291.7    .045       0   311.1     .12       0
#XS Ineff= 2 , 0
                          351.08         1758.09
Permanent Ineff=
       F       F
Bank Sta=291.7,311.1
XS Rating Curve= 0 ,0
Exp/Cntr=0.3,0.1

Type RM Length L Ch R = 1 ,1236.8  ,71.6,83.3,97.3
XS GIS Cut Line= 3
     2054662.994        267495.1      2054445.98      267333.642
     2054456.397       267017.67
#Sta/Elev= 30
       0 1764.34    58.7  1758.2    71.7 1758.34    84.7 1760.48   107.5 1757.18
   130.4 1757.37   140.1 1754.63  193.451749.607   205.3 1748.06   224.9  1748.1
   235.51749.357  261.591751.036   316.1 1750.34   319.4 1749.27   325.9 1743.97
   332.4 1740.88   342.2 1739.78  351.13  1740.9   368.3 1744.59   379.61744.712
   394.3 1747.89   410.6 1747.87  436.641756.095   446.5 1757.61   469.3 1758.39
   508.4 1762.78   534.5 1769.05     554 1768.74   573.6  1772.2   586.6 1773.13
#Mann= 8 ,-1 , 0
       0     .06       0  193.45    .016       0   235.5     .06       0
  261.59     .12       0   332.4    .045       0  351.13     .12       0
   379.6     .06       0  436.64     .12       0
Bank Sta=332.4,351.13
XS Rating Curve= 0 ,0
Exp/Cntr=0.3,0.1

Type RM Length L Ch R = 1 ,1153.5  ,55.3,58.5,63.7
XS GIS Cut Line= 4
     2054702.925      267465.587     2054506.744      267305.864
     2054565.772      267186.073     2054485.911      267010.725
#Sta/Elev= 30
       0 1769.65   32.571762.413    55.1 1759.05    87.6  1755.8   110.3 1757.58
  117.92 1757.13   155.7 1755.33   175.71749.935  201.591747.179  204.931747.024
   217.3 1745.84  265.051746.196   282.3 1744.08   292.1 1739.67   298.6 1737.93
   308.4 1737.61   318.1 1737.92  329.491739.871   337.7 1740.94  348.531740.845
     354 1740.63     367 1742.97  381.451743.475   386.5 1744.23   402.8 1749.53
  413.981751.327   487.8 1753.52   517.2 1758.39  532.731762.878   579.2 1769.46
#Mann= 14 ,-1 , 0
       0     .12       0   32.57     .06       0  117.92     .12       0
   175.7     .06       0  201.59     .08       0  204.93    .016       0
  265.05     .06       0   298.6    .045       0   318.1     .06       0
  329.49    .016       0  348.53     .06       0  381.45     .12       0
  413.98     .06       0  532.73     .12       0
Bank Sta=298.6,318.1
XS Rating Curve= 0 ,0
Exp/Cntr=0.3,0.1

Type RM Length L Ch R = 1 ,1095    ,155,130.3,100.6
XS GIS Cut Line= 4
     2054720.286      267446.489     2054550.147      267311.073
     2054609.175      267191.281     2054529.314      267015.934
#Sta/Elev= 30
       0 1770.39    6.691768.865    35.7 1762.08    87.6 1754.49    97.4 1754.46
   110.4  1756.1  130.551756.565   139.6 1756.33   152.5 1754.62  187.551745.745
   214.2 1745.23  220.021744.631     263 1743.02  269.481740.763  289.181738.116
   295.6 1737.17   305.4 1736.47   315.2  1737.2   324.9 1740.19   331.4 1740.97
   373.9 1740.71  384.181741.976   393.4 1744.53  421.851747.619   445.7 1748.71
     498 1752.44   520.8 1755.93   530.6 1760.13   533.9 1760.68   543.7 1759.55
#Mann= 11 ,-1 , 0
       0     .12       0    6.69     .06       0  130.55     .12       0
  187.55     .08       0  220.02    .016       0  269.48     .12       0
  289.18    .016       0   295.6    .045       0   315.2    .016       0
  384.18     .12       0  421.85     .06       0
Bank Sta=295.6,315.2
XS Rating Curve= 0 ,0
Exp/Cntr=0.3,0.1

Type RM Length L Ch R = 1 ,964.7   ,231.6,221.7,211.8
XS GIS Cut Line= 3
      2054789.73      267378.781     2054666.466      267099.267
     2054544.939      267002.045
#Sta/Elev= 30
       0 1772.22    58.5 1760.93    68.2 1758.39      78 1754.61   84.481753.991
  115.861744.814   146.2  1741.8   178.61740.997   185.2 1739.76     195 1736.31
     208 1736.42   213.5 1735.54   224.2  1733.3     234 1733.47  237.92 1735.54
   240.5 1736.91   243.7  1737.5   253.5 1737.04  276.13 1738.24   308.7 1738.74
  321.771740.966   334.7 1744.29   347.6 1745.98   386.5 1746.65   435.2 1751.65
   441.7 1753.92   444.9 1756.53   448.2 1758.06   454.6 1759.06   461.1 1759.09
#Mann= 8 ,-1 , 0
       0     .06       0   84.48    .016       0  115.86     .06       0
   178.6     .12       0   213.5    .045       0  237.92     .12       0
  276.13    .016       0  321.77     .06       0
#XS Ineff= 2 , 0
                          244.07         1738.61
Permanent Ineff=
       F       F
Bank Sta=213.5,237.92
XS Rating Curve= 0 ,0
Exp/Cntr=0.3,0.1

Type RM Length L Ch R = 1 ,743     ,224.7,219.4,214
XS GIS Cut Line= 2
     2054961.605        267120.1     2054697.716      266887.462
#Sta/Elev= 30
       0  1754.6    22.8 1745.46    42.4 1738.71    48.9  1738.1    55.4 1736.77
    68.4 1736.14  107.84 1736.05   140.1 1735.66   143.3 1735.17   149.8 1733.16
  154.511732.726   159.6 1732.47  163.18 1731.84   166.1 1730.86   172.6 1730.43
   182.4 1730.61   188.9 1731.84   198.7 1732.52   202.31732.439  206.021732.637
   218.2 1732.79   234.5 1734.19   247.6 1734.22  263.051735.165   286.6 1736.57
   293.2 1736.65   309.4 1737.56   332.2 1740.12   345.3 1742.52   351.8 1743.43
#Mann= 8 ,-1 , 0
       0     .12       0  107.84     .06       0  154.51     .12       0
  163.18    .045       0   188.9     .12       0   202.3     .06       0
  206.02    .016       0  263.05     .06       0
#XS Ineff= 2 , 0
                          208.88         1734.48
Permanent Ineff=
       F       F
Bank Sta=163.18,188.9
XS Rating Curve= 0 ,0
Exp/Cntr=0.3,0.1