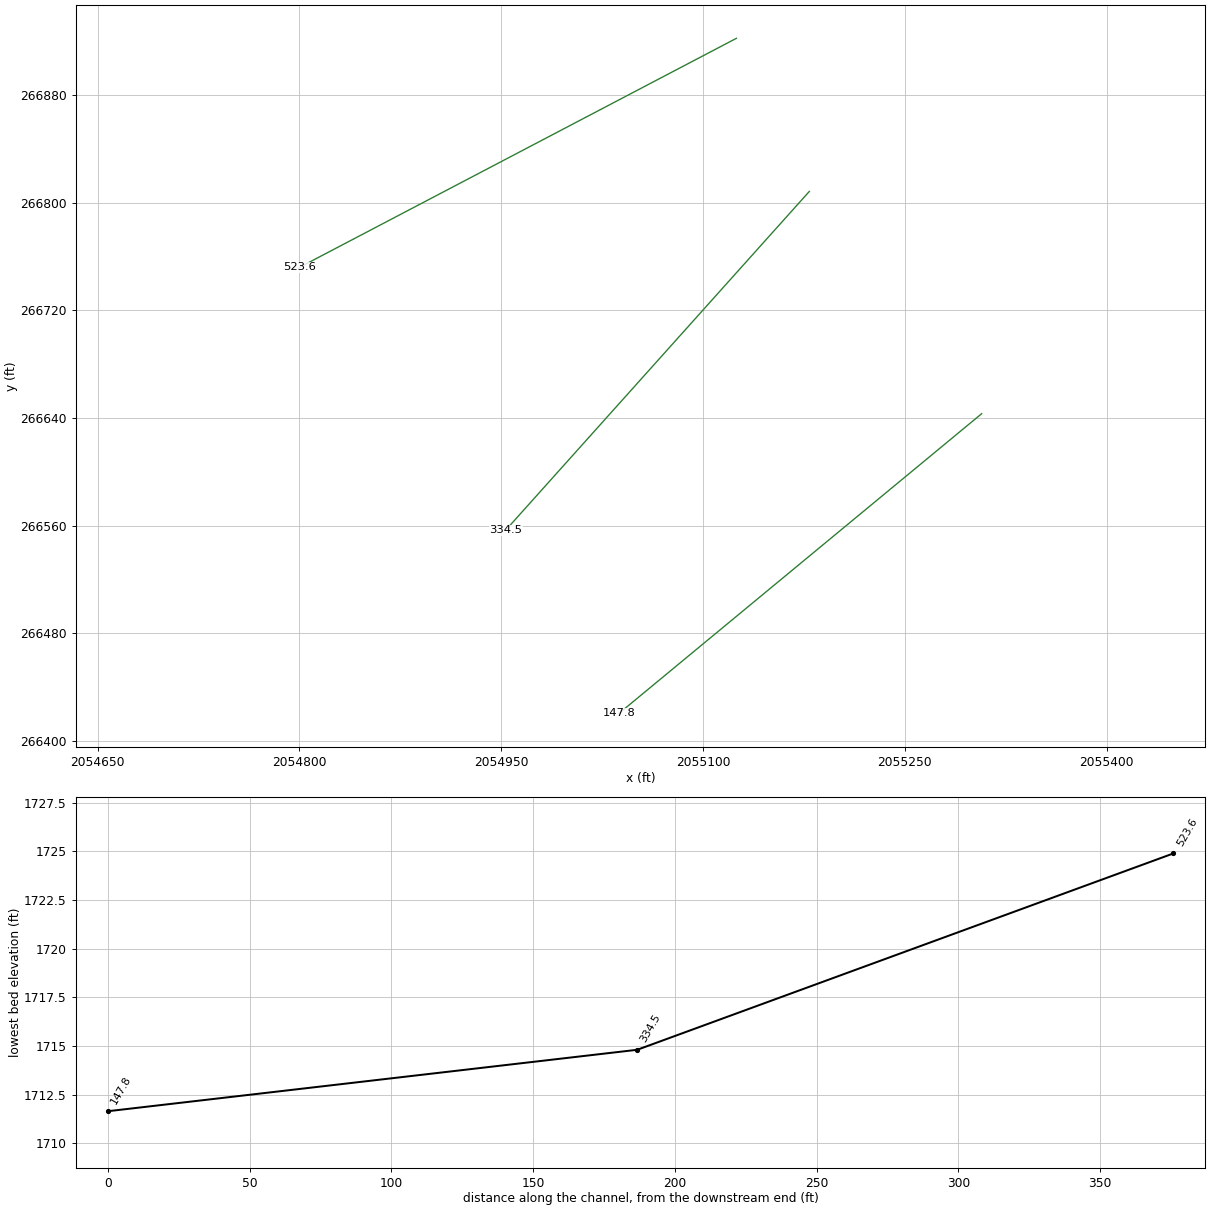
HEC-RAS study GRFTHCK.prj: GRFTHCK

--- GRFTHCK.g01 (geometry) --- (continued)

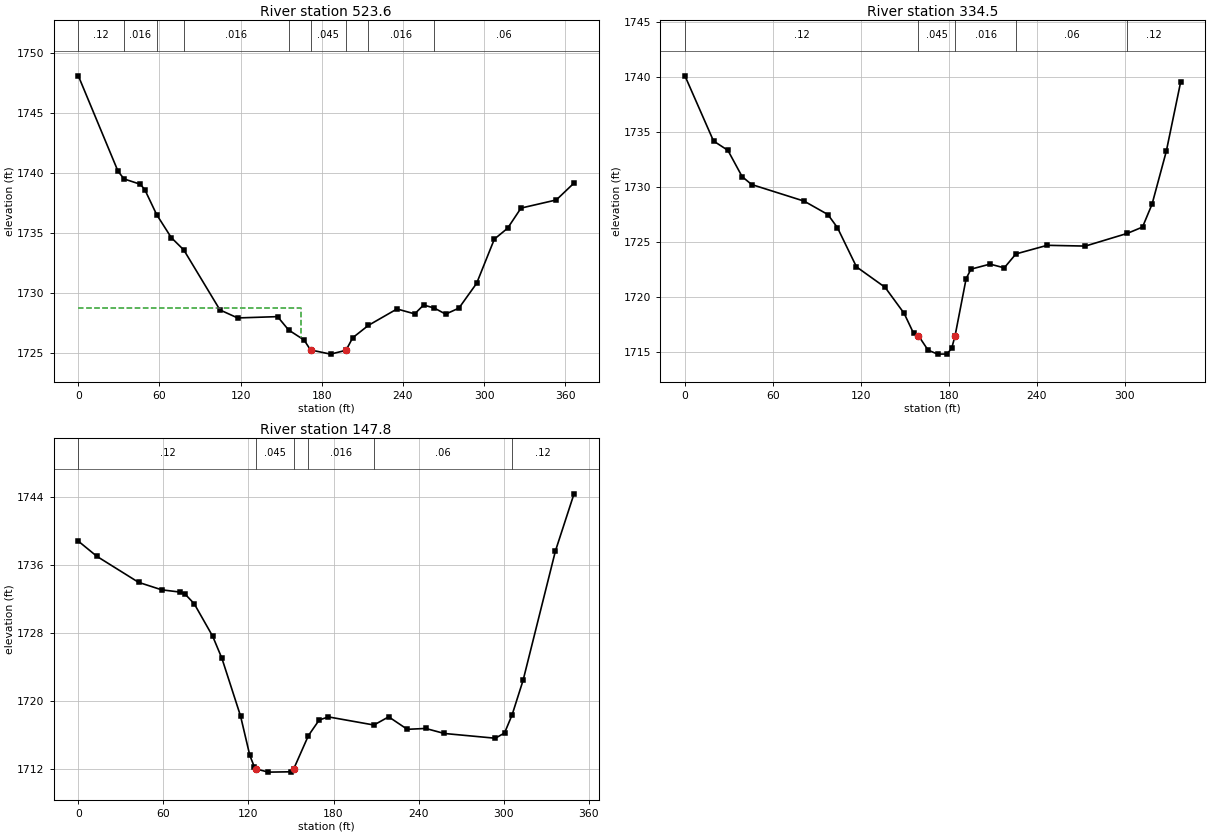
Type RM Length L Ch R = 1 ,523.6   ,180.9,189.1,197.1
XS GIS Cut Line= 2
       2055124.8      266922.184     2054800.147      266752.045
#Sta/Elev= 30
       0 1748.13    29.4 1740.15   33.881739.521    45.8 1739.08    49.1 1738.64
   57.911736.548    68.7 1734.63      781733.592   104.7 1728.59   117.8 1727.92
   147.3 1728.03  155.481726.915   166.9 1726.08  171.67 1725.25   186.5  1724.9
  197.91 1725.22   202.9 1726.27  214.441727.298   235.6 1728.67   248.7 1728.26
   255.3    1729  263.111728.749   271.6 1728.24   281.4 1728.74   294.5 1730.81
   307.6  1734.5   317.4 1735.41   327.3 1737.09   353.4 1737.77   366.5 1739.18
#Mann= 9 ,-1 , 0
       0     .12       0   33.88    .016       0   57.91     .06       0
      78    .016       0  155.48     .12       0  171.67    .045       0
  197.91     .06       0  214.44    .016       0  263.11     .06       0
#XS Ineff= 2 , 0
          164.29 1728.72
Permanent Ineff=
       F       F
Bank Sta=171.67,197.91
XS Rating Curve= 0 ,0
Exp/Cntr=0.3,0.1

Type RM Length L Ch R = 1 ,334.5   ,189.9,186.7,183.2
XS GIS Cut Line= 2
     2055179.053      266808.468     2054953.359      266556.732
#Sta/Elev= 30
       0 1740.12    19.5 1734.19    29.3 1733.34      39 1730.95    45.5 1730.23
    81.3 1728.72    97.5  1727.5     104 1726.31     117 1722.74   136.5 1720.88
   149.5 1718.51     156 1716.68   159.3 1716.47   165.8 1715.17   172.3  1714.8
   178.8 1714.81     182 1715.35  184.28 1716.49   191.8 1721.67   195.1 1722.53
   208.1 1722.99   217.8 1722.65  225.751723.916   247.1  1724.7   273.1 1724.63
  301.741725.786   312.1 1726.36   318.6 1728.44   328.3 1733.24   338.1 1739.55
#Mann= 5 ,-1 , 0
       0     .12       0   159.3    .045       0  184.28    .016       0
  225.75     .06       0  301.74     .12       0
Bank Sta=159.3,184.28
XS Rating Curve= 0 ,0
Exp/Cntr=0.3,0.1

Type RM Length L Ch R = 1 ,147.8   ,148.6,147.8,147.1
XS GIS Cut Line= 2
     2055307.091      266643.249      2055037.56      266420.592
#Sta/Elev= 30
       0 1738.83    13.1 1737.04    42.5 1733.98    58.8  1733.1    71.9 1732.83
    75.2 1732.61    81.7 1731.47    94.8 1727.62   101.3 1725.02   114.4 1718.25
   120.9 1713.64   124.2 1712.22  125.66    1712     134 1711.64   150.3 1711.68
  151.81 1711.98  162.27 1715.94   169.9 1717.78   176.4 1718.14  208.481717.186
   218.9 1718.15     232 1716.68     245 1716.78   258.1 1716.19   294.1 1715.63
   300.6 1716.25  305.941718.384   313.7 1722.46   336.5 1737.68   349.6  1744.4
#Mann= 6 ,-1 , 0
       0     .12       0  125.66    .045       0  151.81     .12       0
  162.27    .016       0  208.48     .06       0  305.94     .12       0
Bank Sta=125.66,151.81
XS Rating Curve= 0 ,0
Exp/Cntr=0.3,0.1

Chan Stop Cuts=-1
Use User Specified Reach Order=0
Composite Channel Slope=5